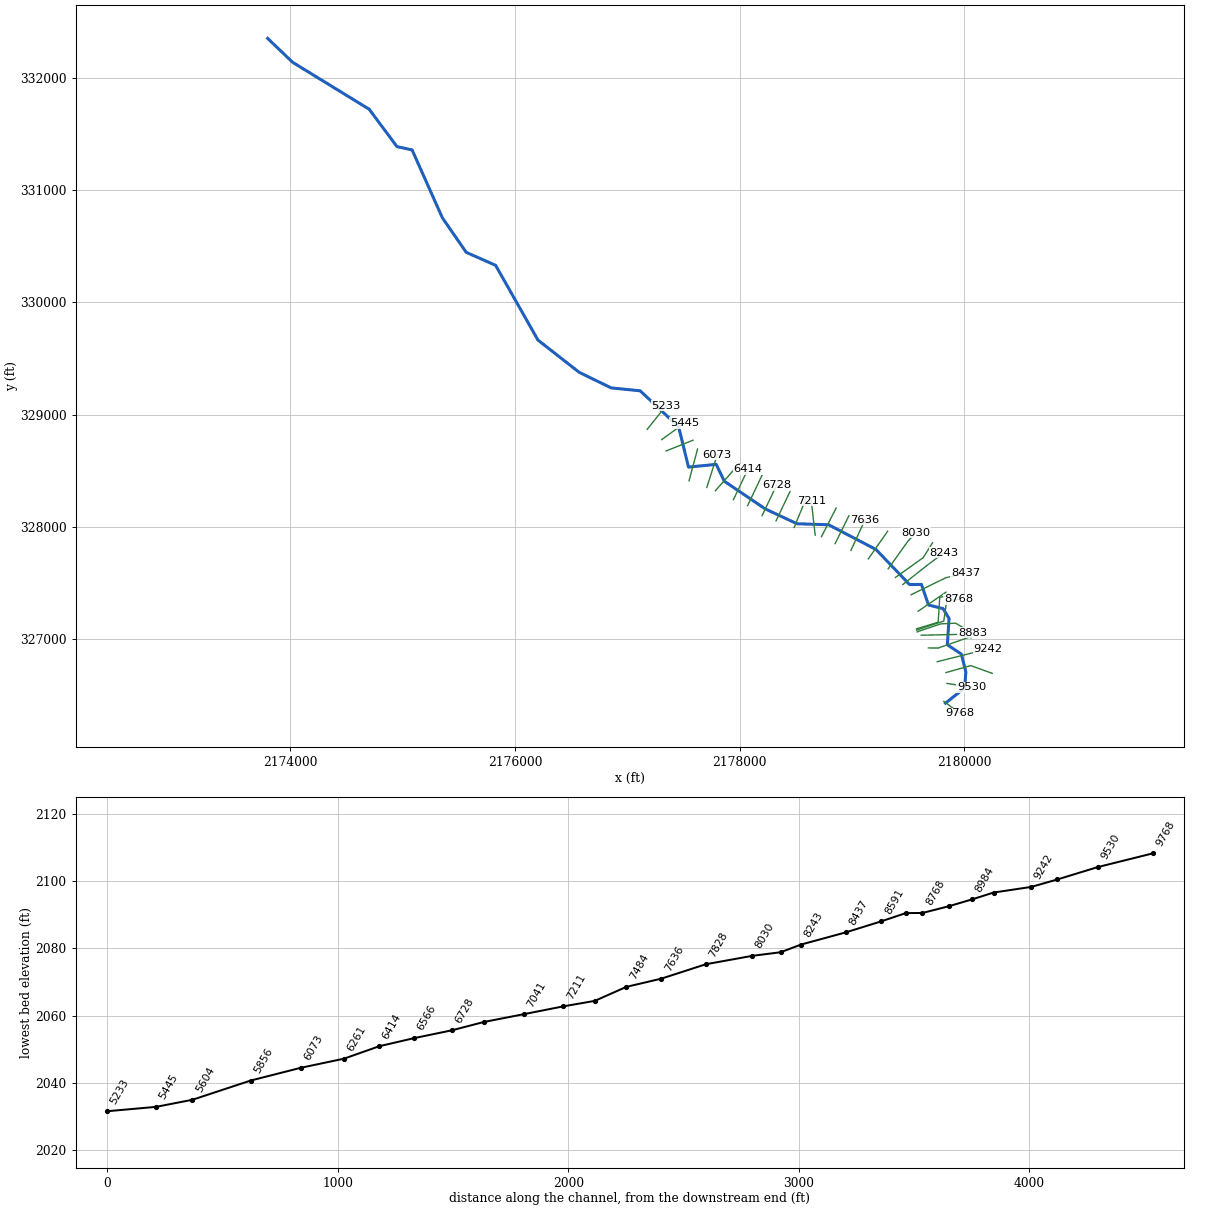
--- ANTNYCKT1.prj (project) ---

Proj Title=ANTNYCKT1
Current Plan=p01
Default Exp/Contr=0,0
English Units
Geom File=g02
Flow File=f02
Plan File=p01
BEGIN DESCRIPTION:
Stream Name- Anthony Creek Tributary 1
Flood Zone: Zone A
Greenbrier County, WV
County-Wide Study
WVDHSEM-2018-3, Flood Risk Project
HEC-RAS Version: 5.0.7
General Notes:
For the Hydrology regression was used.
END DESCRIPTION:
DSS Export Rating Curves= 0
DSS Export Rating Curve Sorted= 0
DSS Export Volume Flow Curves= 0
DXF OffsetX= 0
DXF OffsetY= 0
DXF ScaleX= 0
DXF ScaleY= 0

--- ANTNYCKT1.p01 (plan) ---

Plan Title=Floodplain
Program Version=5.07
Short Identifier=Floodplain
Geom File=g02
Flow File=f02
Subcritical Flow
K Sum by GR= 0
Std Step Tol= 0.01
Critical Tol= 0.01
Num of Std Step Trials= 20
Max Error Tol= 0.3
Flow Tol Ratio= 0.001
Split Flow NTrial= 30
Split Flow Tol= 0.02
Split Flow Ratio= 0.02
Log Output Level= 0
Friction Slope Method= 1
Unsteady Friction Slope Method= 2
Unsteady Bridges Friction Slope Method= 1
Parabolic Critical Depth
Global Vel Dist= 0 , 0 , 0
Global Log Level= 0
CheckData=True
Encroach Param=-1 ,0,0, 0
Mapping Interval=1HOUR
Computation Time Step Use Courant=        0
Computation Time Step Use Time Series=    0
Computation Time Step Count To Double=0
Computation Time Step Max Doubling=0
Computation Time Step Max Halving=0
Computation Time Step Residence Courant=0
Run HTab= 0
Run UNet= 0
Run Sediment= 0
Run PostProcess= 0
Run WQNet= 0
Run RASMapper=-1
UNET Theta= 0
UNET Theta Warmup= 0
UNET ZTol= 0
UNET ZSATol= 0
UNET MxIter= 0
UNET Max Iter WO Improvement= 0
UNET MaxInSteps= 0
UNET DtIC= 0
UNET DtMin= 0
UNET MaxCRTS= 0
UNET WFStab= 0
UNET SFStab= 0
UNET WFX= 1
UNET SFX= 1
UNET 1D Methodology=Finite Difference
UNET DSS MLevel= 1
UNET Pardiso=0
UNET DZMax Abort= 0
UNET Use Existing IB Tables= 0
UNET Froude Reduction=False
UNET Froude Limit= 0
UNET Froude Power= 0
UNET D1 Cores= 0
UNET D2 Coriolis=0
UNET D2 Cores= 0
UNET D2 Theta= 1
UNET D2 Theta Warmup= 1
UNET D2 Z Tol= 0.01
UNET D2 Volume Tol= 0.01
UNET D2 Max Iterations= 20
UNET D2 Equation= 0
UNET D2 RampUpFraction=0.1
UNET D2 TimeSlices= 1
UNET D2 BCVolumeCheck=0
UNET D1D2 MaxIter= 0
UNET D1D2 ZTol=0.01
UNET D1D2 QTol=0.1
UNET D1D2 MinQTol=1
Write IC File= 0
Write IC File at Fixed DateTime=0
Write IC File at Sim End=0
Echo Input=False
Echo Parameters=False
Echo Output=False
Write Detailed= 0
HDF Write Warmup=0
HDF Write Time Slices=0
HDF Flush=0
HDF Face Node Velocities=0
HDF Compression= 1
HDF Chunk Size= 1
HDF Spatial Parts= 1
HDF Use Max Rows=0
HDF Fixed Rows= 1
Calibration Method= 0
Calibration Iterations= 20
Calibration Max Change=0.05
Calibration Tolerance=0.2
Calibration Maximum=1.5
Calibration Minimum=0.5
Calibration Optimization Method= 1
WQ AD Non Conservative
WQ ULTIMATE=-1
WQ Max Comp Step=1HOUR
WQ Output Interval=15MIN
WQ Output Selected Increments= 0
WQ Output face flow=0
WQ Output face velocity=0
WQ Output face area=0
WQ Output face dispersion=0
WQ Output cell volume=0
WQ Output cell surface area=0
WQ Output cell continuity=0
WQ Output cumulative cell continuity=0
WQ Output face conc=0
WQ Output face dconc_dx=0
WQ Output face courant=0
WQ Output face peclet=0
WQ Output face adv mass=0
WQ Output face disp mass=0
WQ Output cell mass=0
WQ Output cell source sink temp=0
WQ Output nsm pathways=0
WQ Output nsm derived pathways=0
WQ Output MaxMinRange=-1
WQ Daily Max Min Mean=-1
WQ Daily Range=0
WQ Daily Time=0
WQ Create Restart=0
WQ Fixed Restart=0
WQ System Summary=0
WQ Write To DSS=0
WQ Use Fixed Temperature=0
Sorting and Armoring Iterations= 10
XS Update Threshold= 0.02
Bed Roughness Predictor= 0
Hydraulics Update Threshold= 0.02
Energy Slope Method= 1
Volume Change Method= 1
Sediment Retention Method= 0
XS Weighting Method= 0
Number of US Weighted Cross Sections= 1
Number of DS Weighted Cross Sections= 1
Upstream XS Weight=0
Main XS Weight=1
Downstream XS Weight=0
Number of DS XS's Weighted with US Boundary= 1
Upstream Boundary Weight= 1
Weight of XSs Associated with US Boundary= 0
Number of US XS's Weighted with DS Boundary= 1
Downstream Boundary Weight= 0.5
Weight of XSs Associated with DS Boundary= 0.5
Percentile Method= 0
Sediment Output Level= 3
Mass or Volume Output= 0
Output Increment Type= 1
Profile and TS Output Increment= 1
XS Output Flag= 0
XS Output Increment= 10
Write Gradation File= 0
Read Gradation Hotstart= 0
Write HDF5 File= 1
Write Binary Output= 1
Write DSS Sediment File= 0
SV Curve= 0
Specific Gage Flag= 0

--- ANTNYCKT1.f02 (steady flow) ---

Flow Title=ANTNYCKT1
Program Version=5.07
Number of Profiles= 6
Profile Names=f1p,f10p,f4p,f2p,f02p,f1pplus
River Rch & RM=ANTNYCKT1,Main            ,9768
     546     288     383     462     763     807
River Rch & RM=ANTNYCKT1,Main            ,8153
     675     359     476     572     940     999
River Rch & RM=ANTNYCKT1,Main            ,7211
     768     410     543     652    1070    1140
River Rch & RM=ANTNYCKT1,Main            ,4360
     859     461     609     730    1190    1270
Boundary for River Rch & Prof#=ANTNYCKT1,Main            , 1
Up Type= 0
Dn Type= 3
Dn Slope=0.0357
Boundary for River Rch & Prof#=ANTNYCKT1,Main            , 2
Up Type= 0
Dn Type= 3
Dn Slope=0.0357
Boundary for River Rch & Prof#=ANTNYCKT1,Main            , 3
Up Type= 0
Dn Type= 3
Dn Slope=0.0357
Boundary for River Rch & Prof#=ANTNYCKT1,Main            , 4
Up Type= 0
Dn Type= 3
Dn Slope=0.0357
Boundary for River Rch & Prof#=ANTNYCKT1,Main            , 5
Up Type= 0
Dn Type= 3
Dn Slope=0.0357
Boundary for River Rch & Prof#=ANTNYCKT1,Main            , 6
Up Type= 0
Dn Type= 3
Dn Slope=0.0357
DSS Import GetInterval= 0
DSS Import GetPeak= 0
DSS Import FillOption= 0

--- ANTNYCKT1.g02 (geometry) ---

Geom Title=ANTNYCKT1
Program Version=5.07

River Reach=ANTNYCKT1       ,Main
Reach XY= 30
     2179833.448326431.8610000162180004.24292226326567.721950337
2180015.10187186 326709.26789546     2179974.795326869.205000013
2179850.24300002326951.9430000192179865.37100004327185.988000005
     2179812.182327273.7240000072179682.09300004327306.476000011
2179619.78300004327489.1820000112179513.62100001327488.311000004
2179215.12300004327800.1819999962178792.95800002328020.590000004
2178511.80000003328029.5630000082178228.57000004328161.987000018
2177864.23799999328408.3540000172177792.21699999328558.424999997
     2177545.251328534.1389999992177457.76504628328892.222838044
     2177115.133329213.3809999972176856.79700001 329239.27700001
2176572.81699999329377.3270000222176204.69100003329665.381000012
2175827.82600002330330.7740000042175566.49400003330446.135000005
2175354.02400003330753.2270000132175084.31400003      331358.103
     2174949.545 331387.527000012174702.37877811331720.346550584
2174020.23200004332138.5320000052173797.74352272332351.744479999

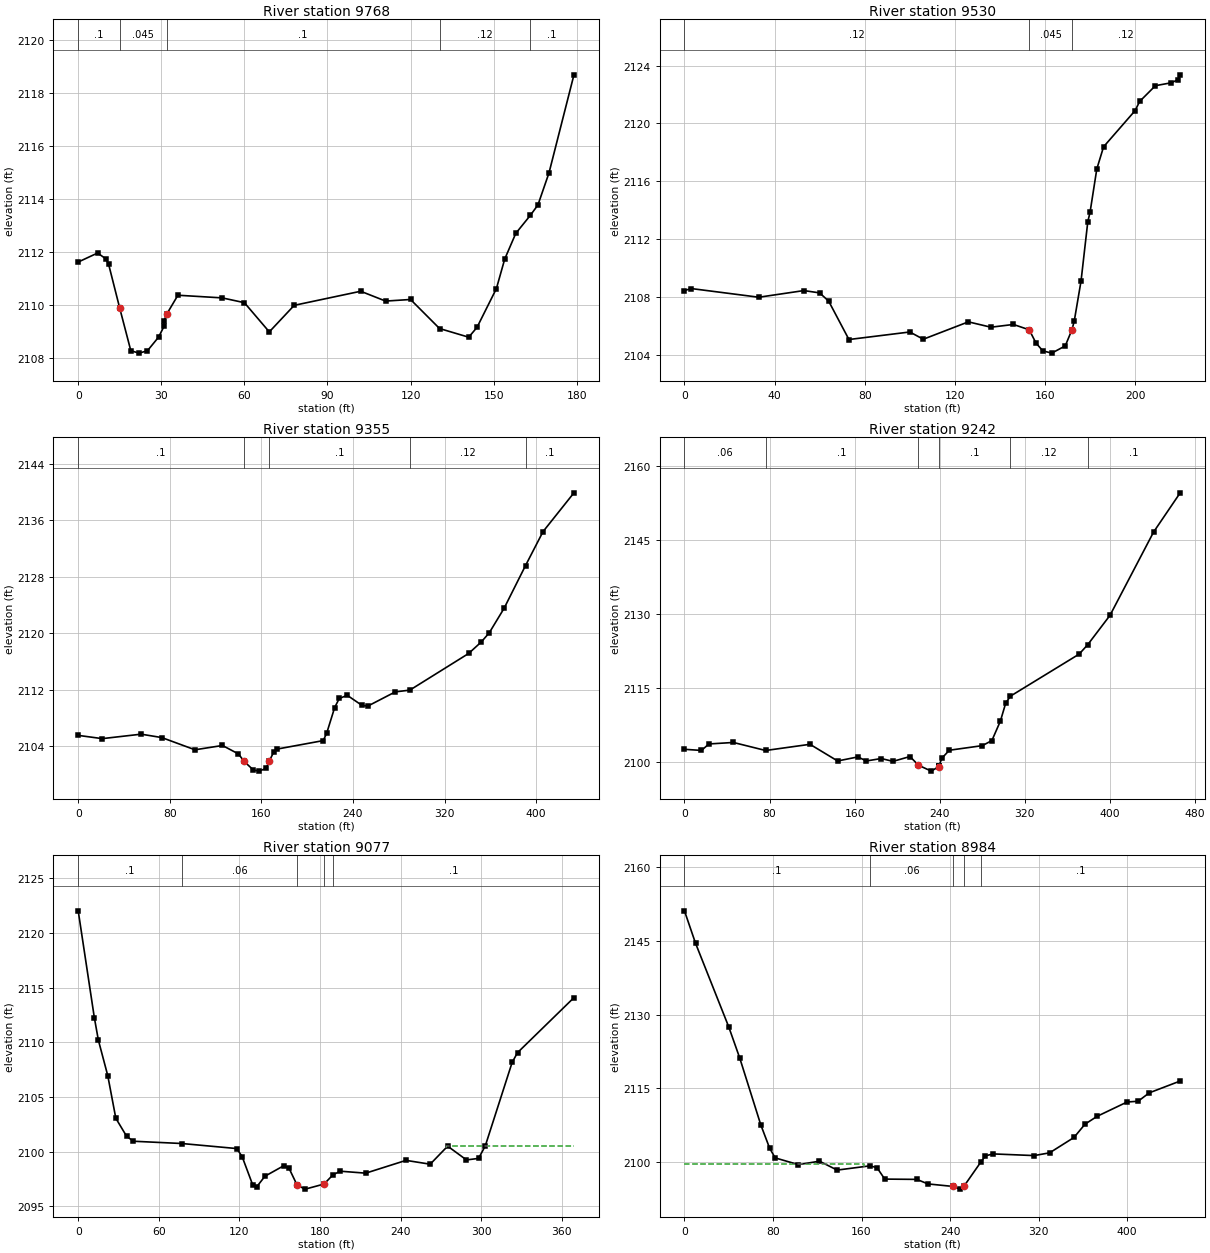
Type RM Length L Ch R = 1 ,9768    ,231,238,241
XS GIS Cut Line= 3
2179819.21251735326448.0029286542179822.36282031326445.662753493
2179963.40413707326341.171169307
#Sta/Elev= 30
       0 2111.63       7 2111.97      10 2111.75      11 2111.54      15 2109.89
      19 2108.29      22  2108.2      25 2108.29      29  2108.8      31 2109.21
      31 2109.42      322109.675      36 2110.38      52 2110.28      60  2110.1
      69    2109      78    2110     102 2110.53     111 2110.16     120 2110.22
  130.482109.126     141  2108.8     144 2109.17     151 2110.63     154 2111.74
     158 2112.71  163.232113.385     166 2113.78     170 2114.99     179 2118.68
#Mann= 5 ,-1 , 0
       0      .1       0      15    .045       0      32      .1       0
  130.48     .12       0  163.23      .1       0
Bank Sta=15,32
XS Rating Curve= 0 ,0
Exp/Cntr(USF)=0,0
Exp/Cntr=0.3,0.1

Type RM Length L Ch R = 1 ,9530    ,168,175,177
XS GIS Cut Line= 2
2179847.61149659326607.6402218362180065.51222798326573.936832026
#Sta/Elev= 30
       0 2108.46       3  2108.6      33    2108      53 2108.46      60  2108.3
      64 2107.73      73 2105.08     100  2105.6     106  2105.1     126  2106.3
     136 2105.93     146 2106.12     153 2105.75     156 2104.84     159  2104.3
     163 2104.14     169 2104.64     172 2105.77     173 2106.37     176 2109.12
     179 2113.22     180 2113.87     183 2116.86     186 2118.39     200 2120.89
     202 2121.52     209 2122.61     216 2122.81     219 2123.02     220 2123.36
#Mann= 3 ,-1 , 0
       0     .12       0     153    .045       0     172     .12       0
Bank Sta=153,172
XS Rating Curve= 0 ,0
Exp/Cntr(USF)=0,0
Exp/Cntr=0.3,0.1

Type RM Length L Ch R = 1 ,9355    ,115,113,114
XS GIS Cut Line= 3
2179837.66845735326704.2762684652180058.71657364326766.564429976
2180249.72607192326697.622851669
#Sta/Elev= 30
       0 2105.53      21 2105.07      55  2105.7      73 2105.22     102 2103.49
     126  2104.1     140  2102.9     1452101.835     153 2100.63     158 2100.47
     164 2100.85     167 2101.94     171 2103.23     174  2103.6     214 2104.79
     217 2105.82     224 2109.47     228 2110.75     235  2111.2     248 2109.76
     253 2109.68     277 2111.69  289.642111.932     341 2117.12     352 2118.74
     359 2120.04     372 2123.52  390.712129.566     406 2134.37     433 2139.86
#Mann= 5 ,-1 , 0
       0      .1       0     145    .045       0     167      .1       0
  289.64     .12       0  390.71      .1       0
Bank Sta=145,167
XS Rating Curve= 0 ,0
Exp/Cntr(USF)=0,0
Exp/Cntr=0.3,0.1

Type RM Length L Ch R = 1 ,9242    ,165,164,167
XS GIS Cut Line= 3
2179760.15489282 326801.210992352180060.47446514326876.945179087
2180212.37952685326912.064304014
#Sta/Elev= 30
       0 2102.66      16 2102.43      23 2103.74      46 2104.04   76.292102.419
     118 2103.67     144  2100.3     163 2101.12     171  2100.3     185  2100.8
     196 2100.22     212  2101.2     220 2099.44     232 2098.25     239 2099.16
     239 2099.19     239  2099.2     239 2099.23     242 2100.87     249 2102.47
     280  2103.4     289 2104.43     297 2108.37     302    2112  306.462113.404
     371 2121.89  379.032123.784     400 2129.72     441 2146.56     466 2154.48
#Mann= 6 ,-1 , 0
       0     .06       0   76.29      .1       0     220    .045       0
     239      .1       0  306.46     .12       0  379.03      .1       0
Bank Sta=220,239
XS Rating Curve= 0 ,0
Exp/Cntr(USF)=0,0
Exp/Cntr=0.3,0.1

Type RM Length L Ch R = 1 ,9077    ,98,94,90
XS GIS Cut Line= 3
2179681.50691539326923.7976028452179769.63638746326923.069316673
2180034.80665898327016.115817647
#Sta/Elev= 30
       0 2122.02      12 2112.26      15  2110.2      22 2106.95      28 2103.05
      36 2101.41      41 2100.95   77.172100.741     118 2100.28     122 2099.55
     130 2096.92     133  2096.8     139 2097.75     153 2098.71     157 2098.46
     163 2096.92     169 2096.57     1832097.035  189.592097.873     195 2098.21
     214 2098.03     244  2099.2     262 2098.85     275  2100.5     289 2099.24
     298 2099.38     303 2100.52     323 2108.16     327 2109.05     369 2114.08
#Mann= 5 ,-1 , 0
       0      .1       0   77.17     .06       0     163    .045       0
     183     .06       0  189.59      .1       0
#XS Ineff= 2 , 0
                          273.94         2100.55
Permanent Ineff=
       F       F
Bank Sta=163,183
XS Rating Curve= 0 ,0
Exp/Cntr(USF)=0,0
Exp/Cntr=0.3,0.1

Type RM Length L Ch R = 1 ,8984    ,100,100,101
XS GIS Cut Line= 3
2179617.51909498327037.0220447372179933.20035451327043.921238709
2180062.09751289 327013.93490713
#Sta/Elev= 30
       0 2151.11      10 2144.53      40 2127.53      50 2121.16      69 2107.59
      77 2102.84      82 2100.88     103 2099.51     122 2100.21     138  2098.4
  167.512099.263     174  2098.9     181 2096.57     210 2096.51     220 2095.59
     243 2095.07     249 2094.53     253 2095.25  267.612099.958     272  2101.3
     279 2101.69     316 2101.35     330 2101.91     352 2105.03     362 2107.74
     373 2109.34     400 2112.24     410  2112.4     420  2114.1     448 2116.51
#Mann= 5 ,-1 , 0
       0      .1       0  167.51     .06       0     243    .045       0
     253     .06       0  267.61      .1       0
#XS Ineff= 2 , 0
          162.25 2099.55
Permanent Ineff=
       F       F
Bank Sta=243,253
XS Rating Curve= 0 ,0
Exp/Cntr=0.3,0.1

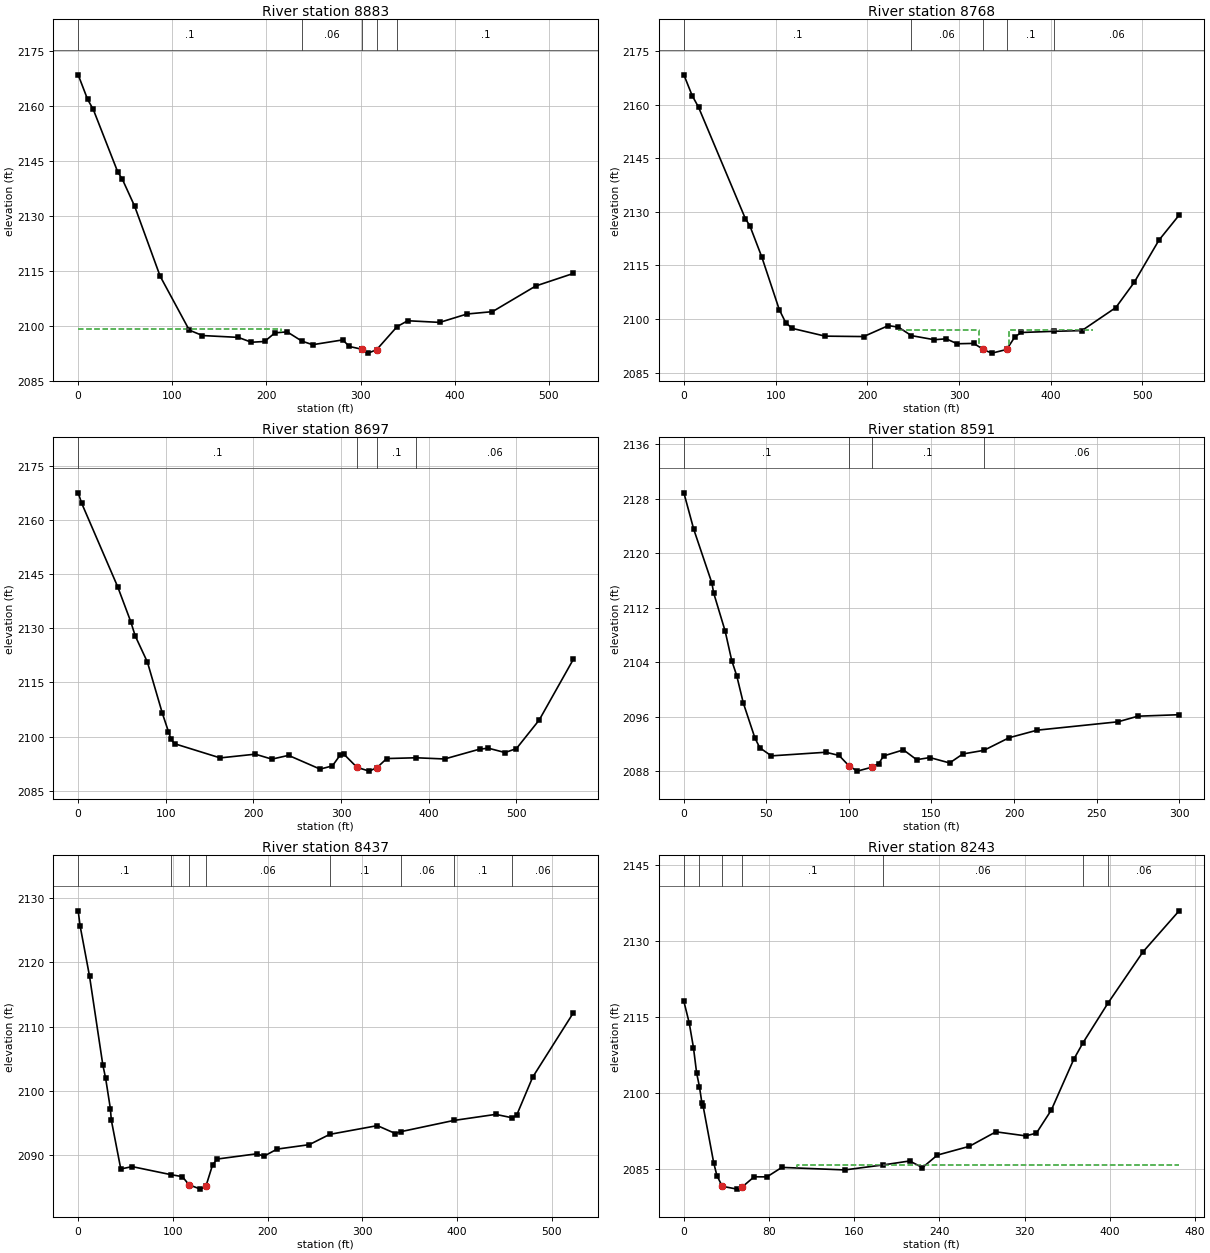
Type RM Length L Ch R = 1 ,8883    ,103,115,131
XS GIS Cut Line= 4
2179581.24515994327066.9099992952179791.60584993327138.424181499
2179923.62940894327144.0729917252180072.63116465327057.836302518
#Sta/Elev= 30
       0 2168.47      10 2161.77      16 2159.04      42 2141.97      47 2139.92
      60 2132.59      87 2113.53     118 2098.78     132  2097.3     170  2096.8
     184 2095.47     198 2095.68     209 2098.04     222  2098.3  237.612095.778
     249  2094.8     281 2096.11     288 2094.32     301 2093.58     301  2093.5
     301 2093.49     308  2092.5     317 2093.44  338.722099.735     350 2101.34
     384 2100.89     413 2103.18     440 2103.82     486 2110.83     526 2114.26
#Mann= 5 ,-1 , 0
       0      .1       0  237.61     .06       0     301    .045       0
     317     .06       0  338.72      .1       0
#XS Ineff= 2 , 0
          215.29 2099.03
Permanent Ineff=
       F       F
Bank Sta=301,317
XS Rating Curve= 0 ,0
Exp/Cntr(USF)=0,0
Exp/Cntr=0.5,0.3

Type RM Length L Ch R = 1 ,8768    ,70,72,67
XS GIS Cut Line= 4
2179576.93195362327082.2994452362179818.35951329327163.523134259
2179844.13769127327340.9334895192179948.64047276327357.268694316
#Sta/Elev= 30
       0 2168.31       9 2162.53      16 2159.25      67 2128.13      72 2126.07
      85 2117.35     104 2102.68     111 2099.03     118 2097.43     154 2095.25
     196 2095.13     223  2098.2     234 2097.76  248.032095.397     273 2094.25
     286  2094.5     298 2093.12     316 2093.22     326 2091.63     326  2091.5
     336  2090.5     352 2091.53     361 2095.08     368 2096.27  403.52  2096.6
     434  2096.8     471 2103.24     491 2110.27     518 2122.08     540 2129.08
#Mann= 5 ,-1 , 0
       0      .1       0  248.03     .06       0     326    .045       0
     352      .1       0  403.52     .06       0
#XS Ineff= 2 ,-1
  233.49  321.41 2096.99  354.93     446 2096.94
Permanent Ineff=
       F       F
Bank Sta=326,352
XS Rating Curve= 0 ,0
Exp/Cntr(USF)=0,0
Exp/Cntr=0.5,0.3

Type RM Length L Ch R = 1 ,8697    ,114,106,100
XS GIS Cut Line= 4
2179575.22967431327093.6156687312179768.41685077 327152.85814295
2179782.73973854327375.6318519942179921.12986122327394.476366366
#Sta/Elev= 30
       0 2167.45       4 2164.56      45 2141.51      60  2131.8      65 2127.91
      79 2120.61      96 2106.48     103 2101.38     106 2099.24     110 2098.04
     162 2094.12     202 2095.15     221 2093.78     240 2094.82     276 2091.02
     290  2091.9     299 2094.94     303 2095.18     3182091.523     332 2090.46
     341 2091.44     352 2093.94  385.662094.156     418 2093.82     458 2096.54
     468  2096.8     487  2095.6     500  2096.7     526 2104.61     565 2121.43
#Mann= 4 ,-1 , 0
       0      .1       0     318    .045       0     341      .1       0
  385.66     .06       0
Bank Sta=318,341
XS Rating Curve= 0 ,0
Exp/Cntr(USF)=0,0
Exp/Cntr=0.5,0.3

Type RM Length L Ch R = 1 ,8591    ,154,154,153
XS GIS Cut Line= 2
2179589.84089641327250.538551896 2179837.5132101327420.086041806
#Sta/Elev= 30
       0 2128.86       6 2123.49      17  2115.6      18  2114.2      25 2108.57
      29 2104.24      32 2102.04      36 2098.02      43 2092.91      46 2091.44
      53 2090.26      86 2090.79      94 2090.32     100  2088.8     105 2088.02
     114  2088.6     114 2088.66     118 2089.12     121 2090.25     133 2091.14
     141  2089.7     149 2090.01     161 2089.22     169 2090.54  181.772091.072
     197 2092.92     214 2094.03     263 2095.26     275 2096.08     300  2096.3
#Mann= 4 ,-1 , 0
       0      .1       0     100    .045       0     114      .1       0
  181.77     .06       0
Bank Sta=100,114
XS Rating Curve= 0 ,0
Exp/Cntr(USF)=0,0
Exp/Cntr=0.3,0.1

Type RM Length L Ch R = 1 ,8437    ,187,194,190
XS GIS Cut Line= 3
2179527.14439544 327397.471559142179837.70934888327549.365024747
2180011.19007437327587.916297078
#Sta/Elev= 30
       0    2128       2 2125.69      12 2117.83      26 2104.07      29 2101.97
      34 2097.25      35 2095.47      45 2087.87      57 2088.24   97.882086.991
     110 2086.68     1172085.423     129 2084.74     135 2085.24     142 2088.55
     147 2089.42     189 2090.24     196 2089.84     210 2090.96     244 2091.65
  265.652093.252     316 2094.61     335 2093.38  340.622093.667  396.412095.408
     441 2096.36  458.222095.833     463 2096.21     480 2102.15     523 2112.16
#Mann= 8 ,-1 , 0
       0      .1       0   97.88     .06       0     117    .045       0
     135     .06       0  265.65      .1       0  340.62     .06       0
  396.41      .1       0  458.22     .06       0
Bank Sta=117,135
XS Rating Curve= 0 ,0
Exp/Cntr(USF)=0,0
Exp/Cntr=0.3,0.1

Type RM Length L Ch R = 1 ,8243    ,89,89,88
XS GIS Cut Line= 3
2179453.62155157327488.3925803062179689.22902949327674.105036392
2179822.04789449327772.239567914
#Sta/Elev= 30
       0 2118.07       5 2113.85       9 2108.97      12 2103.96   14.622101.272
      17 2097.99      18 2097.56      28 2086.32      31 2083.79      36 2081.68
      50 2081.12      55 2081.59      66 2083.55      78 2083.53      92  2085.4
     151  2084.9     187 2085.88     212 2086.66     224 2085.36     238 2087.82
     268 2089.54     293  2092.4     321  2091.6     331 2092.14     345 2096.68
     366 2106.64  374.882109.971  398.152117.716     431  2127.8     465  2135.9
#Mann= 7 ,-1 , 0
       0      .1       0   14.62      .1       0      36    .045       0
      55      .1       0     187     .06       0  374.88      .1       0
  398.15     .06       0
#XS Ineff= 2 , 0
                          106.05         2085.85
Permanent Ineff=
       F       F
Bank Sta=36,55
XS Rating Curve= 0 ,0
Exp/Cntr(USF)=0,0
Exp/Cntr=0.3,0.1

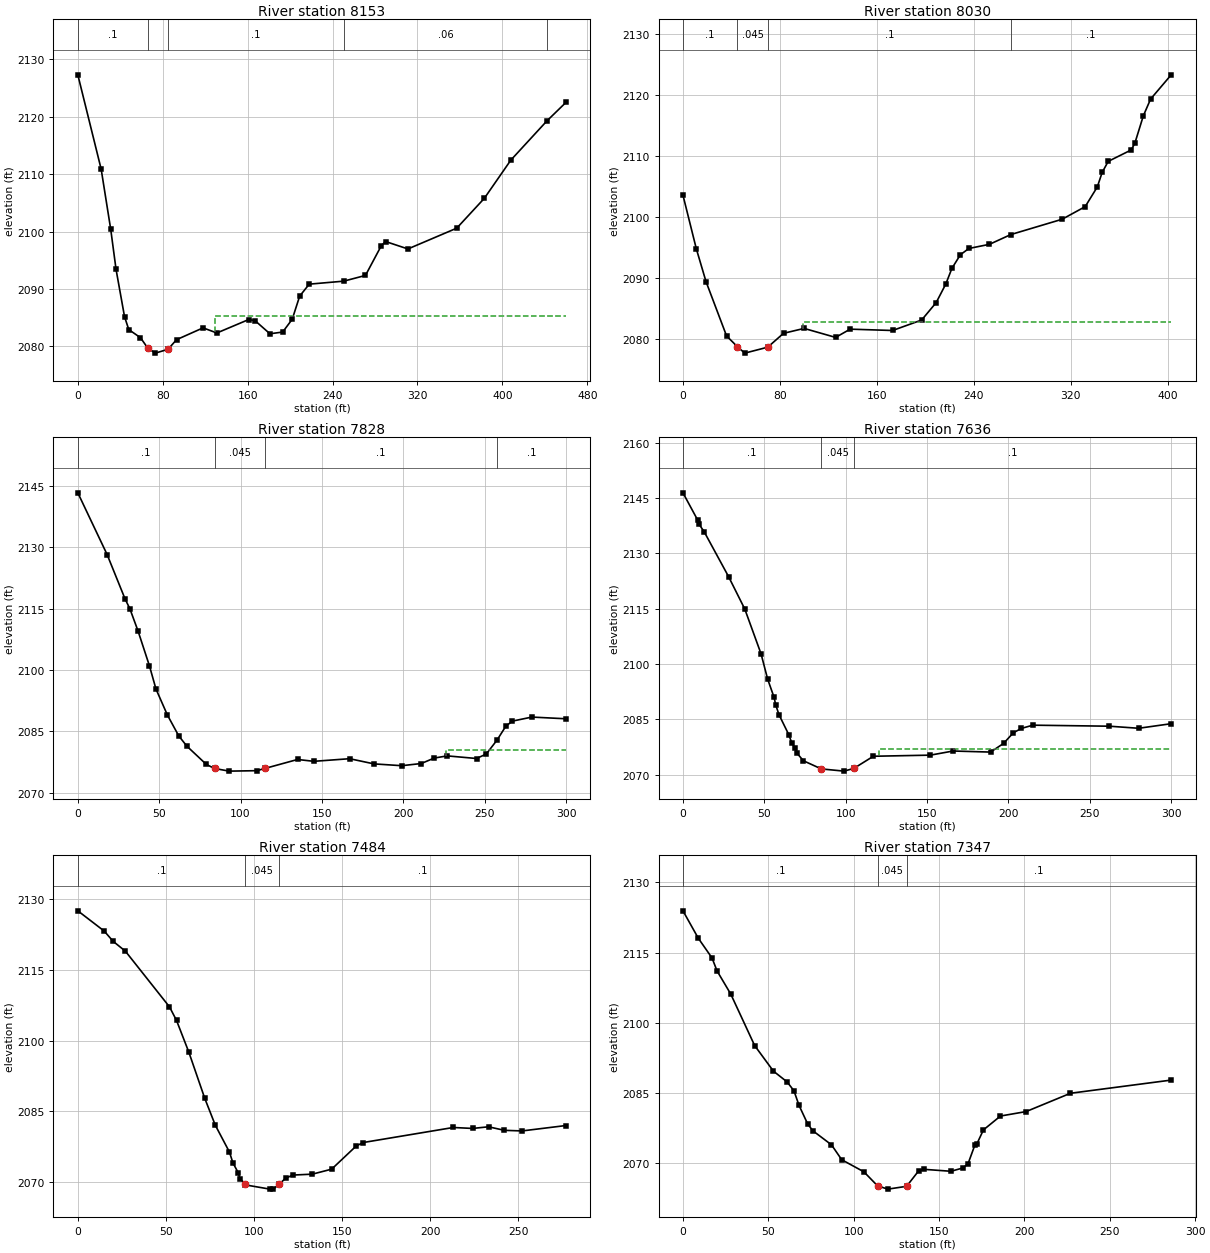
Type RM Length L Ch R = 1 ,8153    ,121,123,127
XS GIS Cut Line= 3
2179388.26397869327551.4281686632179635.31516914327727.664659281
 2179718.4413501327860.184657921
#Sta/Elev= 30
       0 2127.29      22 2110.85      31 2100.38      36 2093.42      44 2085.18
      48 2082.93      59 2081.52      66 2079.68      73 2078.83      85  2079.5
      93 2081.17     118 2083.23     131 2082.34     161 2084.68     167 2084.48
     181  2082.2     193  2082.5     202 2084.73     209 2088.75     218 2090.84
  250.522091.362     271 2092.36     286 2097.56     290 2098.26     311 2096.97
     357 2100.59     383 2105.79     408 2112.45  441.97 2119.27     460 2122.51
#Mann= 5 ,-1 , 0
       0      .1       0      66    .045       0      85      .1       0
  250.52     .06       0  441.97      .1       0
#XS Ineff= 1 ,-1
  128.87   459.9 2085.32
Permanent Ineff=
       F
Bank Sta=66,85
XS Rating Curve= 0 ,0
Exp/Cntr(USF)=0,0
Exp/Cntr=0.3,0.1

Type RM Length L Ch R = 1 ,8030    ,200,201,200
XS GIS Cut Line= 3
2179323.46725165327628.1960714362179497.74037624327872.386321129
2179567.85044255327948.129747927
#Sta/Elev= 30
       0 2103.58      11 2094.84      19 2089.47      36 2080.57      452078.795
      51 2077.76      702078.733      83    2081     100  2081.8     126 2080.33
     138 2081.68     173 2081.46     197 2083.17     209 2086.02     217 2089.08
     222 2091.62     229 2093.85     236 2094.87     253 2095.55  270.622097.145
     313 2099.65     332 2101.71     342 2104.93     346  2107.3     351 2109.11
     370 2110.98     373 2112.08     380 2116.56     386  2119.3     403 2123.26
#Mann= 4 ,-1 , 0
       0      .1       0      45    .045       0      70      .1       0
  270.62      .1       0
#XS Ineff= 2 , 0
                           99.15         2082.83
Permanent Ineff=
       F       F
Bank Sta=45,70
XS Rating Curve= 0 ,0
Exp/Cntr(USF)=0,0
Exp/Cntr=0.3,0.1

Type RM Length L Ch R = 1 ,7828    ,188,193,194
XS GIS Cut Line= 2
2179146.19590143327716.8221139372179318.47189966327962.586475052
#Sta/Elev= 30
       0 2143.38      18 2128.27      29 2117.43      32 2114.99      37 2109.56
      44 2101.04      48 2095.38      55 2089.03      62  2083.9      67 2081.38
      79  2076.9      84 2075.92      93 2075.27     110 2075.38     115 2075.93
     135 2078.12     145 2077.67     167 2078.31     182 2077.04     199  2076.6
     211 2077.13     219 2078.47     227    2079     245 2078.36     251 2079.47
  257.592082.874     263 2086.27     267 2087.51     279  2088.5     300 2088.08
#Mann= 4 ,-1 , 0
       0      .1       0      84    .045       0     115      .1       0
  257.59      .1       0
#XS Ineff= 2 , 0
                          226.42          2080.5
Permanent Ineff=
       F       F
Bank Sta=84,115
XS Rating Curve= 0 ,0
Exp/Cntr(USF)=0,0
Exp/Cntr=0.3,0.1

Type RM Length L Ch R = 1 ,7636    ,152,152,152
XS GIS Cut Line= 2
2178992.12871868327793.1529237252179117.49785026328065.701232923
#Sta/Elev= 30
       0 2146.39       9 2139.04      10 2137.81      13 2135.87      28 2123.71
      38 2114.89      48 2102.74      52 2095.97      56 2090.95      57 2088.93
      59 2086.28      65 2080.89      67 2078.49      69  2077.2      70 2075.88
      74  2073.8      85 2071.59      99 2070.99     105 2071.73     117 2075.02
     152 2075.32     166 2076.44     189 2076.15     197  2078.5     203 2081.38
     208 2082.57     215 2083.44     262 2083.16     280  2082.6     300 2083.84
#Mann= 3 ,-1 , 0
       0      .1       0      85    .045       0     105      .1       0
#XS Ineff= 2 , 0
                          120.48            2077
Permanent Ineff=
       F       F
Bank Sta=85,105
XS Rating Curve= 0 ,0
Exp/Cntr(USF)=0,0
Exp/Cntr=0.3,0.1

Type RM Length L Ch R = 1 ,7484    ,138,137,137
XS GIS Cut Line= 2
2178851.03772264327852.9562943592178973.57833321328101.128895974
#Sta/Elev= 30
       0 2127.51      15 2123.21      20 2121.06      27 2118.95      52 2107.16
      56 2104.28      63 2097.54      72 2087.79      78 2082.08      86 2076.41
      88  2074.1      91 2072.01      92 2070.67      95 2069.72      95 2069.44
     109 2068.54     111 2068.55     114 2069.54     118 2070.87     122 2071.52
     133 2071.71     144 2072.77     158  2077.7     162 2078.42     213  2081.6
     224  2081.4     233 2081.75     242    2081     252 2080.87     277 2082.02
#Mann= 3 ,-1 , 0
       0      .1       0      95    .045       0     114      .1       0
Bank Sta=95,114
XS Rating Curve= 0 ,0
Exp/Cntr(USF)=0,0
Exp/Cntr=0.3,0.1

Type RM Length L Ch R = 1 ,7347    ,129,136,139
XS GIS Cut Line= 2
2178729.36026934327914.3973846372178860.09482469328169.219001086
#Sta/Elev= 30
       0 2123.92       9 2118.05      17 2113.85      20 2111.04      28 2106.11
      42 2095.09      53 2089.62      61 2087.32      65 2085.43      68 2082.29
      73 2078.37      76 2076.89      87 2073.86      93 2070.67     106 2068.08
     114 2065.08     120 2064.38     131 2064.98     138 2068.26     141 2068.62
     157  2068.2     164 2068.91     167 2069.82     171 2073.82     172 2073.93
     176 2077.05     186 2080.02     201 2080.97     227 2084.89     286 2087.71
#Mann= 3 ,-1 , 0
       0      .1       0     114    .045       0     131      .1       0
Bank Sta=114,131
XS Rating Curve= 0 ,0
Exp/Cntr(USF)=0,0
Exp/Cntr=0.3,0.1

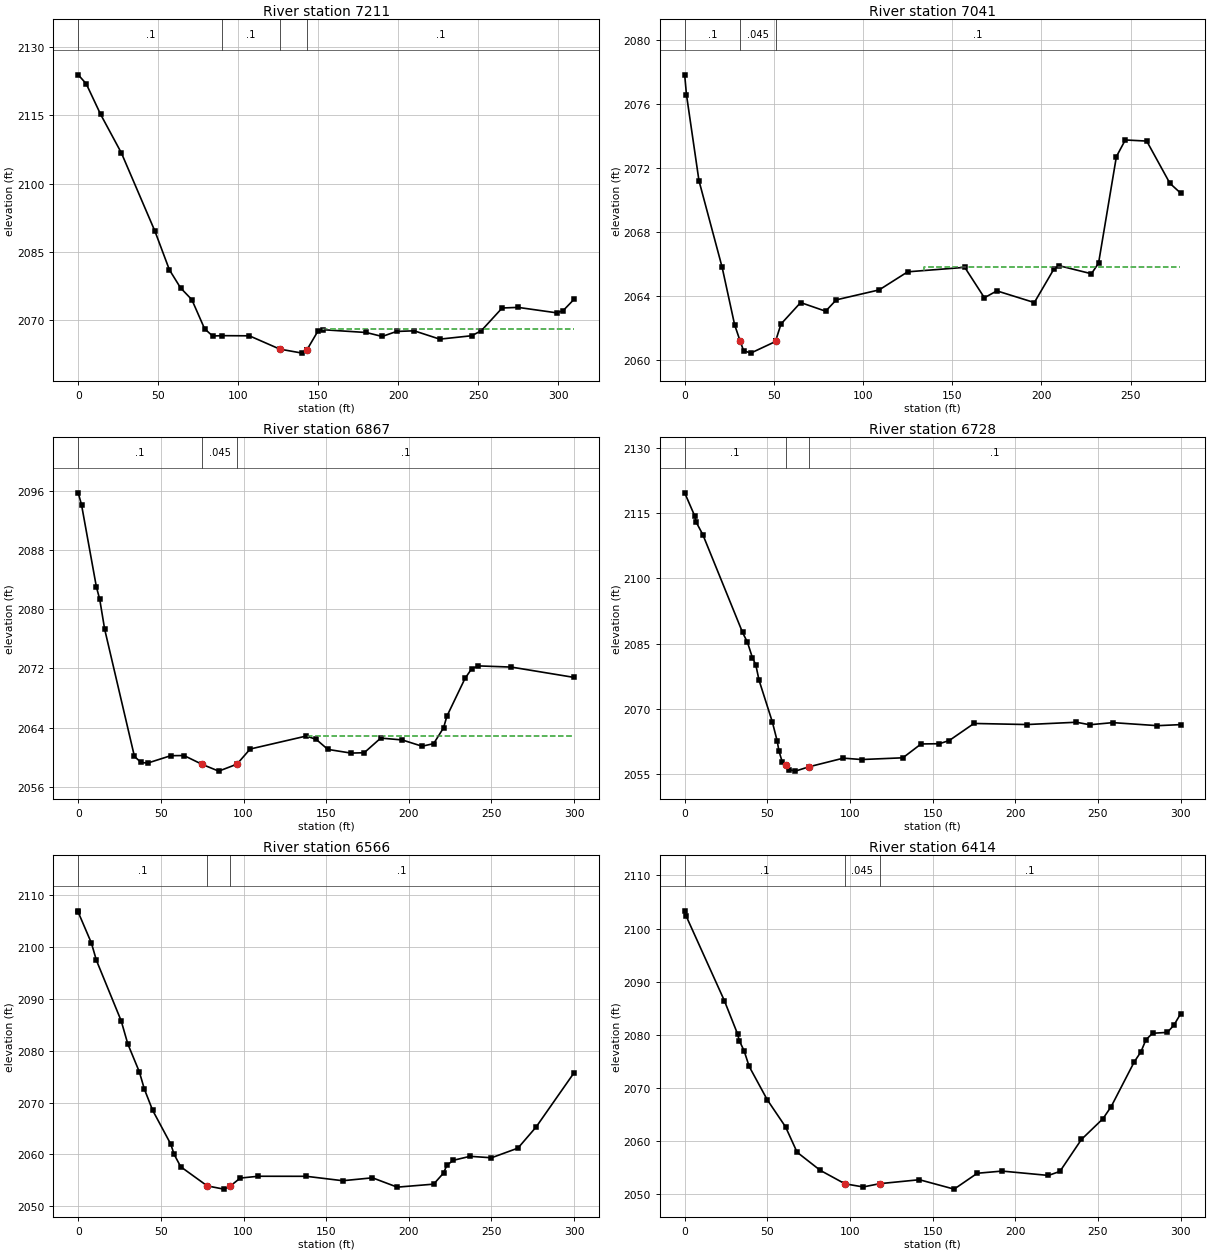
Type RM Length L Ch R = 1 ,7211    ,174,171,163
XS GIS Cut Line= 2
2178673.44532424327927.8981300622178638.29848868328236.214952532
#Sta/Elev= 30
       0 2123.86       5  2121.9      14 2115.18      27  2106.7      48 2089.49
      57 2081.05      64 2077.07      71 2074.51      79 2068.11      84 2066.52
   90.072066.596     107 2066.56     126 2063.64     140 2062.76     143 2063.37
     143  2063.5     150 2067.69     153  2067.9     180 2067.29     190 2066.42
     199 2067.52     210 2067.66     226 2065.83     246 2066.58     252 2067.69
     265 2072.67     275  2072.8     299 2071.61     303 2072.05     310  2074.6
#Mann= 4 ,-1 , 0
       0      .1       0   90.07      .1       0     126    .045       0
     143      .1       0
#XS Ineff= 2 , 0
                          153.23         2068.08
Permanent Ineff=
       F       F
Bank Sta=126,143
XS Rating Curve= 0 ,0
Exp/Cntr(USF)=0,0
Exp/Cntr=0.3,0.1

Type RM Length L Ch R = 1 ,7041    ,173,174,172
XS GIS Cut Line= 2
2178486.57868535327996.847779188 2178591.4943587328253.776171471
#Sta/Elev= 30
       0 2077.83       1 2076.59       8 2071.22      21  2065.8      28 2062.21
      31 2061.22      33  2060.6      37 2060.44      51 2061.17      51  2061.2
      51 2061.21      54 2062.26      65  2063.6      79 2063.06      85 2063.77
     109 2064.39     125 2065.52     157  2065.8     168  2063.9     175 2064.33
     196  2063.6     207  2065.7     210  2065.9     228  2065.4     232 2066.06
     242 2072.72     247 2073.76     259 2073.69     272 2071.05     278 2070.44
#Mann= 3 ,-1 , 0
       0      .1       0      31    .045       0      51      .1       0
#XS Ineff= 1 ,-1
  133.88   277.5  2065.8
Permanent Ineff=
       F
Bank Sta=31,51
XS Rating Curve= 0 ,0
Exp/Cntr(USF)=0,0
Exp/Cntr=0.3,0.1

Type RM Length L Ch R = 1 ,6867    ,137,139,139
XS GIS Cut Line= 2
2178324.86394962328055.5154658392178453.86012398328326.365954119
#Sta/Elev= 30
       0 2095.77       2 2094.16      11 2083.03      13 2081.37      16 2077.31
      34 2060.11      38 2059.28      42  2059.2      56  2060.2      64 2060.22
      75 2059.02      85 2058.11      96 2059.05     104  2061.1     138 2062.86
     144  2062.4     151 2061.05     165 2060.55     173  2060.6     183 2062.58
     196 2062.33     208 2061.48     215 2061.83     221 2063.97     223 2065.53
     234 2070.66     238 2071.96     242 2072.35     262 2072.19     300 2070.79
#Mann= 3 ,-1 , 0
       0      .1       0      75    .045       0      96      .1       0
#XS Ineff= 2 , 0
                          139.27          2062.9
Permanent Ineff=
       F       F
Bank Sta=75,96
XS Rating Curve= 0 ,0
Exp/Cntr(USF)=0,0
Exp/Cntr=0.3,0.1

Type RM Length L Ch R = 1 ,6728    ,162,163,162
XS GIS Cut Line= 2
2178200.76550362 328101.981964112178329.76167798328372.832452389
#Sta/Elev= 30
       0 2119.73       6 2114.47       7 2112.94      11 2110.08      35 2087.58
      38 2085.27      41 2081.72      43 2080.13      45 2076.55      53 2066.99
      56 2062.51      57 2060.29      59 2057.77      61 2056.94      63 2055.97
      67 2055.63      75 2056.61      96 2058.62     107  2058.3     132  2058.7
     143 2061.89     154 2061.94     160 2062.67     175 2066.61     207 2066.36
     237 2066.89     245 2066.31     259  2066.8     286  2066.1     300 2066.34
#Mann= 3 ,-1 , 0
       0      .1       0      61    .045       0      75      .1       0
#XS Ineff= 2 , 0
                           96.37         2058.59
Permanent Ineff=
       F       F
Bank Sta=61,75
XS Rating Curve= 0 ,0
Exp/Cntr(USF)=0,0
Exp/Cntr=0.3,0.1

Type RM Length L Ch R = 1 ,6566    ,151,152,152
XS GIS Cut Line= 2
2178071.73682562328191.3307393942178200.73299998328462.181227673
#Sta/Elev= 30
       0 2106.93       0 2106.67       8 2100.71      11  2097.4      26 2085.73
      30 2081.29      37 2075.89      40  2072.6      45 2068.52      56 2061.98
      58 2060.03      62 2057.63      78 2053.95      88 2053.32      92 2053.91
      98 2055.45     109  2055.8     138 2055.79     160 2054.94     178  2055.5
     193  2053.7     215 2054.28     221 2056.42     223 2057.93     227 2058.88
     237 2059.64     250 2059.36     266 2061.22     277 2065.29     300 2075.76
#Mann= 3 ,-1 , 0
       0      .1       0      78    .045       0      92      .1       0
Bank Sta=78,92
XS Rating Curve= 0 ,0
Exp/Cntr(USF)=0,0
Exp/Cntr=0.3,0.1

Type RM Length L Ch R = 1 ,6414    ,155,153,150
XS GIS Cut Line= 2
2177945.45517917328244.7033717012178074.45135353 328515.55385998
#Sta/Elev= 30
       0 2103.33       1 2102.27      24 2086.41      32 2080.13      33  2078.9
      36 2076.91      39 2074.02      50 2067.71      61 2062.64      68 2057.85
      82 2054.44      97  2051.9     108 2051.31     118 2051.93     142 2052.67
     163  2050.9     177 2053.89     192  2054.3     220 2053.48     227 2054.24
     240 2060.26     253 2064.16     258 2066.45     272  2074.9     276 2076.77
     279 2079.03     283 2080.26     292 2080.43     296 2081.82     300 2083.93
#Mann= 3 ,-1 , 0
       0      .1       0      97    .045       0     118      .1       0
Bank Sta=97,118
XS Rating Curve= 0 ,0
Exp/Cntr(USF)=0,0
Exp/Cntr=0.3,0.1

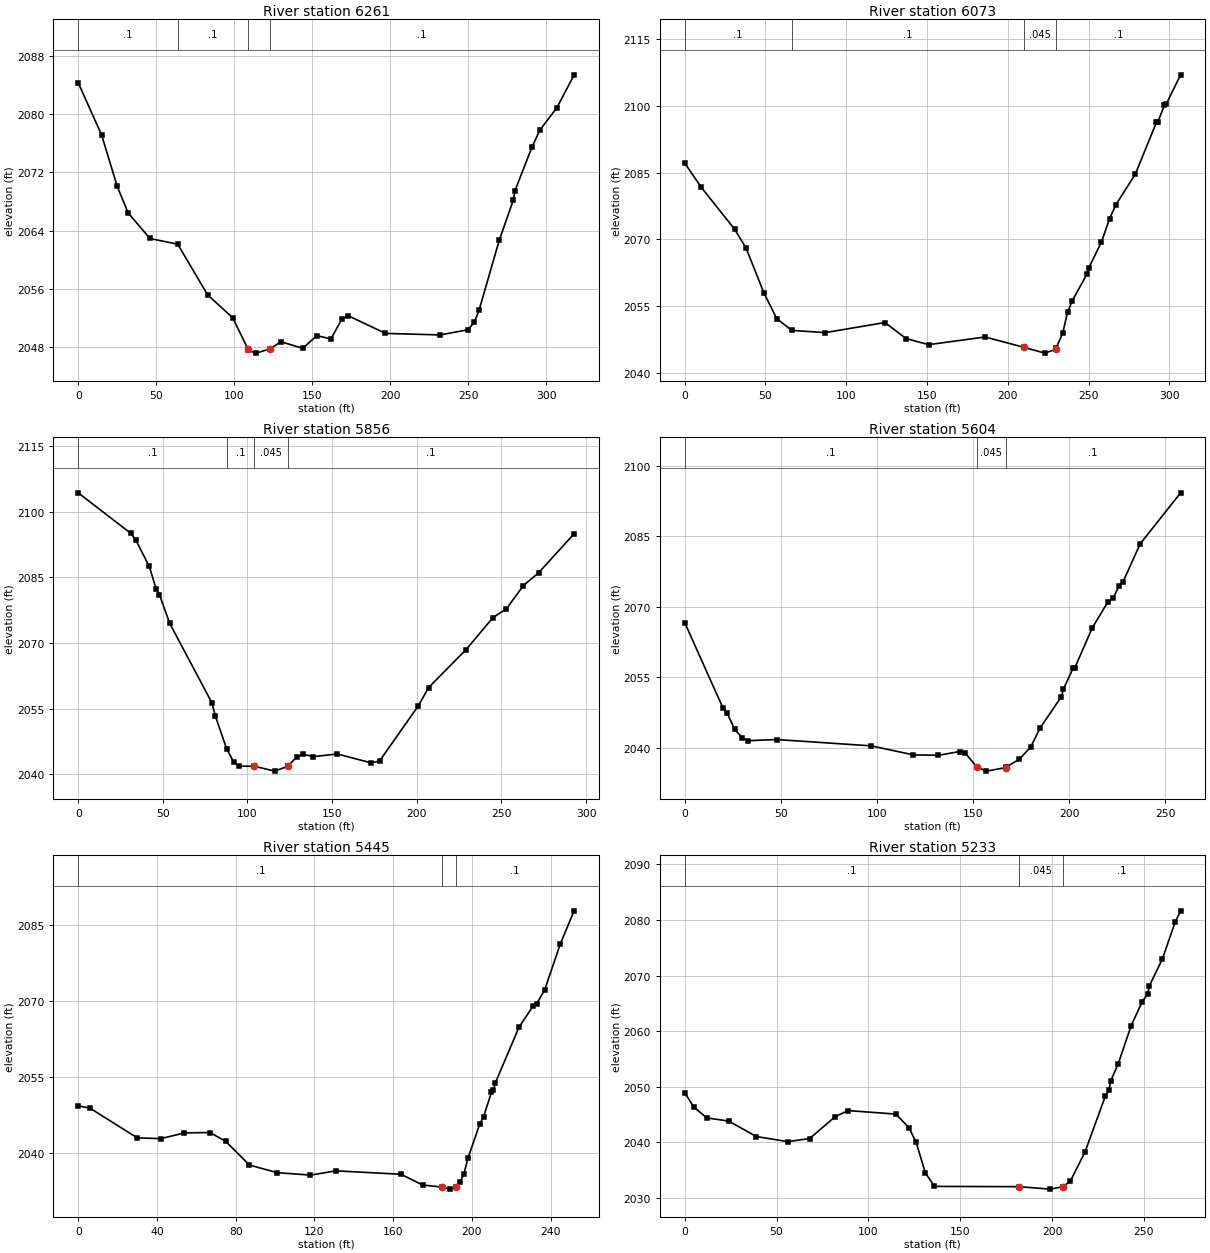
Type RM Length L Ch R = 1 ,6261    ,179,187,190
XS GIS Cut Line= 2
2177783.93154006328323.2677019912177995.28821655328561.159052738
#Sta/Elev= 30
       0 2084.32      15 2077.15      25  2070.1      32 2066.45      46 2062.94
    63.82062.154      83 2055.19      99 2052.07     109 2047.71     109 2047.57
     114  2047.2     123 2047.78     130 2048.76     144 2047.86     153  2049.6
     162 2049.15     169 2051.84     173 2052.35     197 2049.91     232  2049.7
     250 2050.41     254 2051.47     257 2053.07     270 2062.71     279 2068.23
     280 2069.47     291 2075.51     296 2077.82     307 2080.92     318 2085.41
#Mann= 4 ,-1 , 0
       0      .1       0    63.8      .1       0     109    .045       0
     123      .1       0
Bank Sta=109,123
XS Rating Curve= 0 ,0
Exp/Cntr(USF)=0,0
Exp/Cntr=0.3,0.1

Type RM Length L Ch R = 1 ,6073    ,214,218,215
XS GIS Cut Line= 2
2177708.39238474328352.7715528582177801.57769121328644.851984881
#Sta/Elev= 30
       0 2087.14      10  2081.8      31 2072.24      38 2068.06      49 2058.04
      57 2052.23   66.292049.597      87  2049.1     124 2051.36     137 2047.77
     151  2046.4     186 2048.12     210  2045.8     223  2044.5     230  2045.4
     230 2045.69     234 2048.96     237 2053.68     240  2056.3     249 2062.19
     250 2063.49     258 2069.43     263 2074.62     267 2077.81     279 2084.67
     292 2096.22     293 2096.42     297 2100.12     298 2100.29     307  2106.9
#Mann= 4 ,-1 , 0
       0      .1       0   66.29      .1       0     210    .045       0
     230      .1       0
Bank Sta=210,230
XS Rating Curve= 0 ,0
Exp/Cntr(USF)=0,0
Exp/Cntr=0.3,0.1

Type RM Length L Ch R = 1 ,5856    ,261,252,242
XS GIS Cut Line= 2
2177550.08214329328411.3245995912177625.84461732328694.763598273
#Sta/Elev= 30
       0 2104.28      31 2095.05      34  2093.5      42 2087.46      46 2082.35
      48 2081.02      54  2074.5      79  2056.3      81 2053.31   87.672045.811
      92 2042.71      95 2041.82     1042041.825     116  2040.7     124 2041.82
     124 2041.86     129 2043.91     133 2044.55     139 2044.01     153 2044.62
     173  2042.6     178 2042.99     201 2055.65     207  2059.8     229 2068.39
     245 2075.77     253 2077.78     263 2083.09     272 2086.02     293 2094.93
#Mann= 4 ,-1 , 0
       0      .1       0   87.67      .1       0     104    .045       0
     124      .1       0
Bank Sta=104,124
XS Rating Curve= 0 ,0
Exp/Cntr(USF)=0,0
Exp/Cntr=0.3,0.1

Type RM Length L Ch R = 1 ,5604    ,158,158,158
XS GIS Cut Line= 2
2177346.33337444328678.1944677082177586.07409925328773.367921277
#Sta/Elev= 30
       0 2066.63      20 2048.36      22 2047.46      26 2043.88      30 2042.09
      33 2041.49      48 2041.72      97 2040.38     119 2038.46     132 2038.37
     143 2039.17     146 2038.83     152 2035.86     157    2035     167 2035.75
     167 2035.81     174  2037.5     180 2040.13     185 2044.24     196 2050.87
     197 2052.42     202 2056.86     203 2057.03     212 2065.46     220 2070.91
     223 2071.94     226 2074.42     228 2075.27     237 2083.41     258 2094.24
#Mann= 3 ,-1 , 0
       0      .1       0     152    .045       0     167      .1       0
Bank Sta=152,167
XS Rating Curve= 0 ,0
Exp/Cntr(USF)=0,0
Exp/Cntr=0.3,0.1

Type RM Length L Ch R = 1 ,5445    ,210,212,212
XS GIS Cut Line= 2
2177306.70917967328778.9315452972177510.99517036328926.448007483
#Sta/Elev= 30
       0 2049.35       6 2048.88      30 2043.02      42 2042.86      54    2044
      67 2044.07      75  2042.3      87 2037.65     101 2036.15     118 2035.66
     131  2036.5     164 2035.83     175 2033.71     185 2033.28     189 2032.89
     192 2033.35     194 2034.23     196 2035.93     198 2038.97     204 2045.72
     206 2047.23     210 2052.04     211 2052.48     212 2053.91     224  2064.9
     231 2068.97     233 2069.55     237 2072.22     245 2081.37     252 2087.86
#Mann= 3 ,-1 , 0
       0      .1       0     185    .045       0     192      .1       0
Bank Sta=185,192
XS Rating Curve= 0 ,0
Exp/Cntr(USF)=0,0
Exp/Cntr=0.3,0.1

Type RM Length L Ch R = 1 ,5233    ,156,157,156
XS GIS Cut Line= 2
2177177.21210198328869.8748550312177345.80345555329080.276864284
#Sta/Elev= 30
       0 2048.94       5 2046.33      12  2044.4      24 2043.82      39 2041.05
      56 2040.13      68 2040.68      82 2044.63      89 2045.71     115 2045.08
     122 2042.66     126 2040.03     131 2034.53     136 2032.08     182 2032.03
     199 2031.59     206 2032.02     210 2033.05     218 2038.31     229 2048.29
     231 2049.42     232 2051.11     236 2054.09     243 2060.93     249 2065.23
     252 2066.68     253 2068.16     260 2072.91     267  2079.6     270 2081.63
#Mann= 3 ,-1 , 0
       0      .1       0     182    .045       0     206      .1       0
Bank Sta=182,206
XS Rating Curve= 0 ,0
Exp/Cntr(USF)=0,0
Exp/Cntr=0.3,0.1