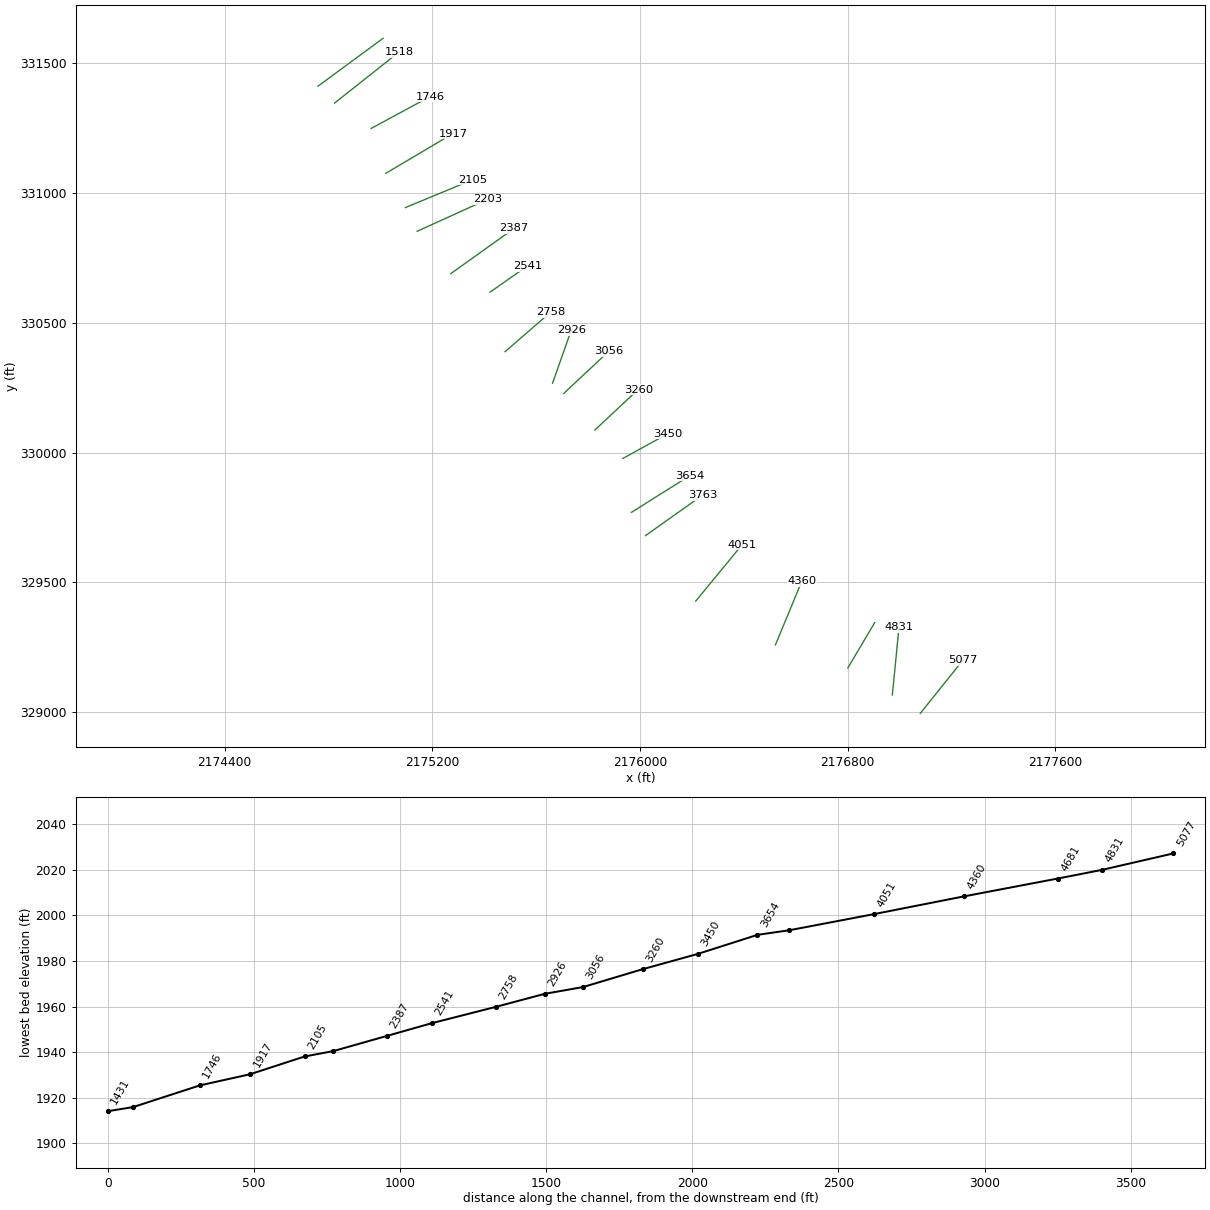
HEC-RAS study ANTNYCKT1.prj: ANTNYCKT1

--- ANTNYCKT1.g02 (geometry) --- (continued)

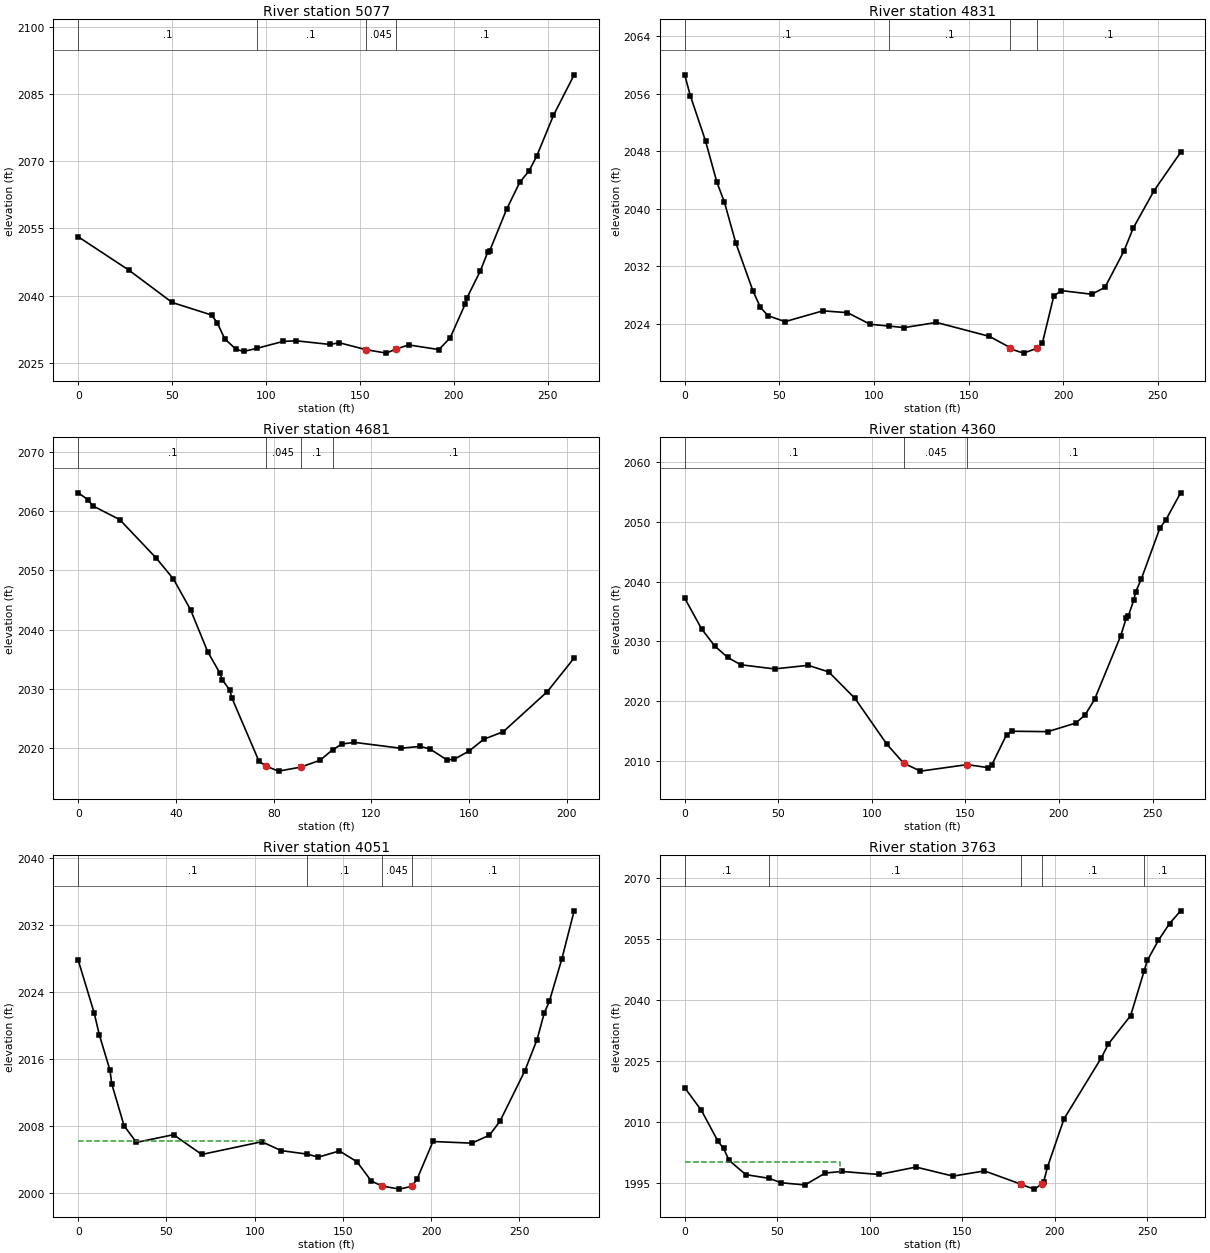
Type RM Length L Ch R = 1 ,5077    ,241,246,249
XS GIS Cut Line= 2
2177080.09164264328995.5218636252177245.06294693 329201.40605137
#Sta/Elev= 30
       0 2053.15      27 2045.69      50 2038.48      71 2035.68      74 2033.96
      78 2030.36      84 2028.03      88 2027.55   95.022028.233     109 2029.78
     116 2029.92     134 2029.11     139 2029.49     153 2027.96     164 2027.17
     169 2028.07     176    2029     192 2027.96     198 2030.59     206 2038.13
     207 2039.57     214 2045.46     218 2049.72     219 2049.97     228 2059.25
     235 2065.27     240 2067.88     244 2071.09     253 2080.27     264 2089.31
#Mann= 4 ,-1 , 0
       0      .1       0   95.02      .1       0     153    .045       0
     169      .1       0
Bank Sta=153,169
XS Rating Curve= 0 ,0
Exp/Cntr(USF)=0,0
Exp/Cntr=0.3,0.1

Type RM Length L Ch R = 1 ,4831    ,154,150,148
XS GIS Cut Line= 2
2176972.41985369329066.755593517 2176998.1671962329327.542461045
#Sta/Elev= 30
       0 2058.61       3  2055.7      11 2049.43      17 2043.69      21 2040.89
      27 2035.23      36  2028.6      40 2026.27      44 2025.11      53 2024.28
      73 2025.78      86 2025.53      98 2023.91  108.022023.661     116 2023.45
     133 2024.17     161 2022.23     172 2020.66     172  2020.5     179  2019.9
     186 2020.56     189 2021.33     195 2027.84     199  2028.6     215 2028.09
     222 2029.04     232 2034.06     237 2037.31     248 2042.51     262 2047.83
#Mann= 4 ,-1 , 0
       0      .1       0  108.02      .1       0     172    .045       0
     186      .1       0
Bank Sta=172,186
XS Rating Curve= 0 ,0
Exp/Cntr(USF)=0,0
Exp/Cntr=0.3,0.1

Type RM Length L Ch R = 1 ,4681    ,319,321,321
XS GIS Cut Line= 2
2176801.07048789329170.7303538872176904.81530502 329345.50931602
#Sta/Elev= 30
       0 2063.06       4  2061.9       6 2060.86      17 2058.54      32 2052.03
      39 2048.52      46 2043.33      53 2036.27      58 2032.65      59 2031.54
      62 2029.81      63 2028.39      74  2017.8      77 2016.96      82 2016.14
      91 2016.81      99 2017.97  104.182019.757     108 2020.71     113 2020.99
     132    2020     140 2020.31     144 2019.87     151 2018.01     154 2018.16
     160 2019.53     166 2021.51     174 2022.79     192 2029.53     203 2035.22
#Mann= 4 ,-1 , 0
       0      .1       0      77    .045       0      91      .1       0
  104.18      .1       0
Bank Sta=77,91
XS Rating Curve= 0 ,0
Exp/Cntr(USF)=0,0
Exp/Cntr=0.3,0.1

Type RM Length L Ch R = 1 ,4360    ,312,309,303
XS GIS Cut Line= 2
2176522.05445229329259.3869853172176623.45260247329504.041913295
#Sta/Elev= 30
       0 2037.23       9 2032.11      16 2029.25      23 2027.32      30 2026.09
      48  2025.4      66    2026      77 2024.89      91 2020.47     108 2012.82
     117 2009.64     126 2008.31     151  2009.4     162  2008.9     164 2009.28
     172  2014.4     175 2014.98     194 2014.91     209 2016.35     214 2017.72
     219 2020.29     233 2030.94     236 2033.95     237  2034.2     240 2036.93
     241 2038.28     244 2040.44     254 2049.01     257 2050.25     265 2054.84
#Mann= 3 ,-1 , 0
       0      .1       0     117    .045       0     151      .1       0
Bank Sta=117,151
XS Rating Curve= 0 ,0
Exp/Cntr(USF)=0,0
Exp/Cntr=0.3,0.1

Type RM Length L Ch R = 1 ,4051    ,291,288,286
XS GIS Cut Line= 2
2176214.99655409329428.0642289262176393.74572868329645.169761539
#Sta/Elev= 30
       0 2027.84       9 2021.58      12  2018.9      18  2014.7      19 2013.07
      26 2008.06      33 2006.08      54    2007      70 2004.64     104 2006.16
     115  2005.1  129.742004.682     136 2004.32     148 2005.06     158 2003.76
     166 2001.48     172 2000.88     182  2000.5     189 2000.84     192  2001.7
     201 2006.19     223 2005.99     233 2006.94     239 2008.62     253  2014.6
     260 2018.37     264 2021.49     267 2022.96     274 2027.98     281 2033.74
#Mann= 4 ,-1 , 0
       0      .1       0  129.74      .1       0     172    .045       0
     189      .1       0
#XS Ineff= 2 , 0
          105.88 2006.22
Permanent Ineff=
       F       F
Bank Sta=172,189
XS Rating Curve= 0 ,0
Exp/Cntr(USF)=0,0
Exp/Cntr=0.3,0.1

Type RM Length L Ch R = 1 ,3763    ,111,109,106
XS GIS Cut Line= 2
2176021.62122639329680.3326338042176240.26280502329835.551239261
#Sta/Elev= 30
       0 2018.43       9 2012.87      18 2005.25      21 2003.49      24 2000.55
      33 1997.04   45.711996.122      52 1995.04      65  1994.5      76 1997.43
      85 1997.82     105 1997.07     125  1998.9     145 1996.67     162 1997.95
     182 1994.64     182 1994.57     189 1993.47     193 1994.72     194 1995.25
     196 1998.83     205 2010.77     225 2025.65     229 2029.21     241 2036.18
   248.32047.163     250 2049.73     256 2054.69     262  2058.8     268 2061.95
#Mann= 5 ,-1 , 0
       0      .1       0   45.71      .1       0     182    .045       0
     193      .1       0   248.3      .1       0
#XS Ineff= 2 , 0
           83.74 2000.26
Permanent Ineff=
       F       F
Bank Sta=182,193
XS Rating Curve= 0 ,0
Exp/Cntr(USF)=0,0
Exp/Cntr=0.3,0.1

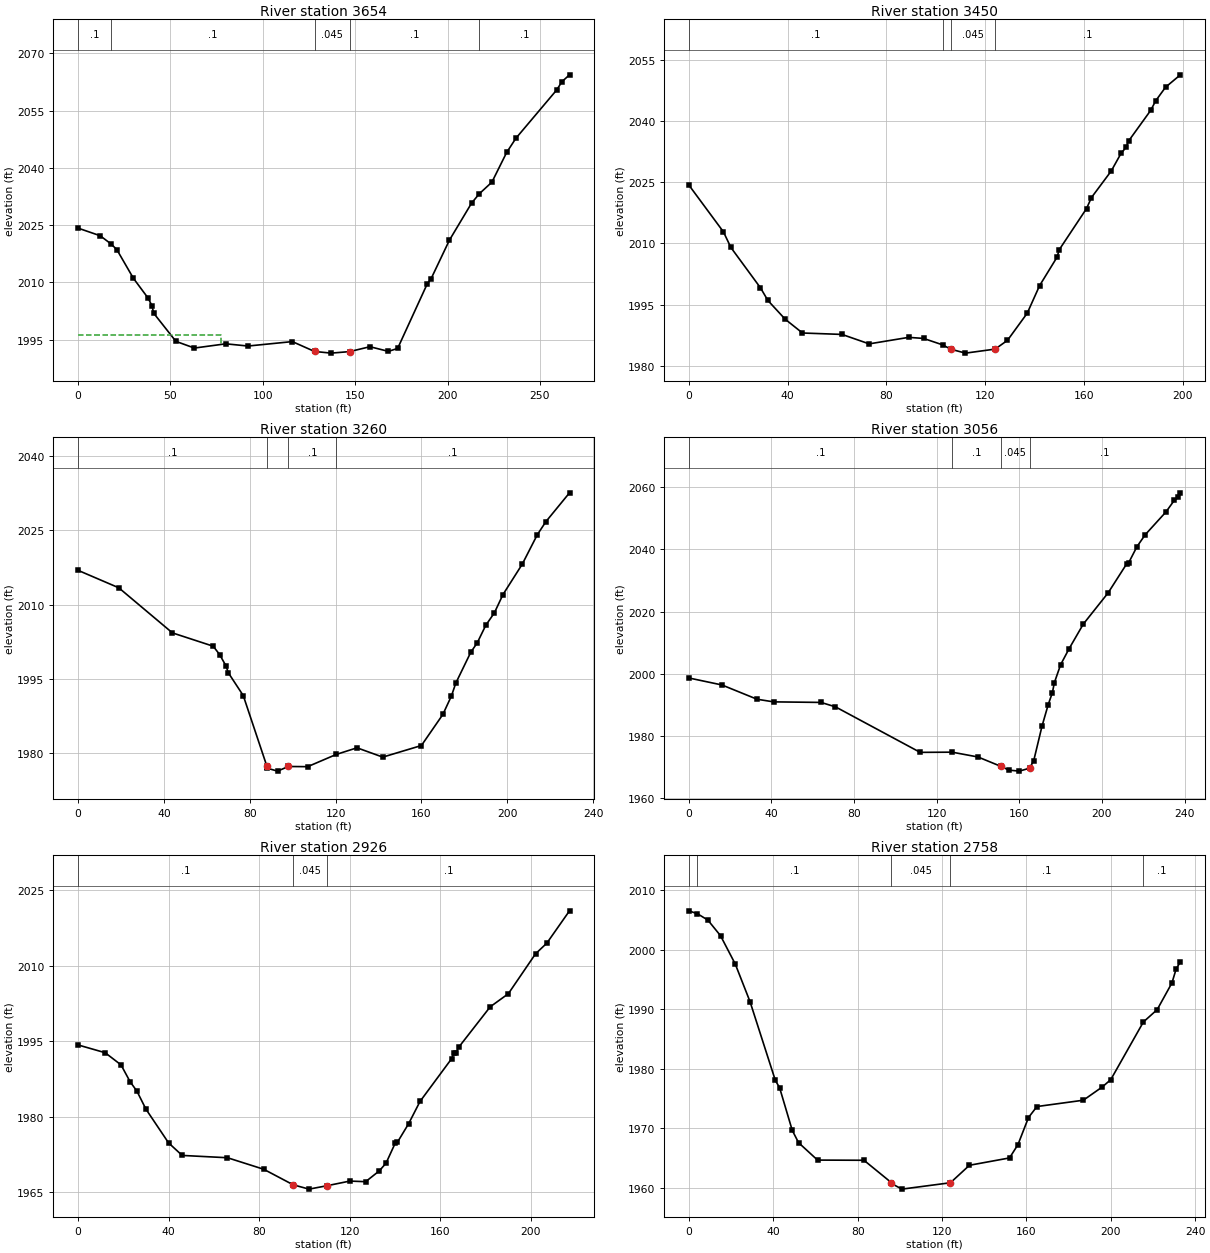
Type RM Length L Ch R = 1 ,3654    ,204,204,202
XS GIS Cut Line= 2
2175967.38214911329769.9276919062176192.47882986329911.380659098
#Sta/Elev= 30
       0 2024.21      12 2022.21   17.842020.077      21 2018.59      30 2011.05
      38 2005.83      40 2003.88      41 2001.89      53 1994.53      63 1992.78
      80 1993.89      92 1993.31     116 1994.47     128 1991.89     137 1991.45
     147 1991.85     158 1993.13     168 1991.91     173 1992.69     189 2009.59
     191 2010.85     201 2021.04     213 2030.75  217.132033.176     224 2036.25
     232 2044.04     237 2047.75     259 2060.37     262 2062.62     266 2064.37
#Mann= 5 ,-1 , 0
       0      .1       0   17.84      .1       0     128    .045       0
     147      .1       0  217.13      .1       0
#XS Ineff= 2 , 0
           77.55 1996.13
Permanent Ineff=
       F       F
Bank Sta=128,147
XS Rating Curve= 0 ,0
Exp/Cntr(USF)=0,0
Exp/Cntr=0.3,0.1

Type RM Length L Ch R = 1 ,3450    ,188,189,193
XS GIS Cut Line= 2
2175934.69448398329977.7680617522176108.78303096330073.584832679
#Sta/Elev= 30
       0 2024.34      14 2012.85      17 2009.03      29 1999.11      32 1996.01
      39 1991.41      46 1988.03      62 1987.68      73 1985.36      89 1986.96
      95  1986.7  102.79 1985.11     106 1984.06     112 1983.09     124 1984.08
     129 1986.23     137  1992.9     142 1999.66     149 2006.58     150 2008.52
     161 2018.57     163 2021.28     171 2027.79     175 2032.15     177 2033.58
     178 2035.13     187 2042.69     189 2045.02     193 2048.36     199  2051.4
#Mann= 4 ,-1 , 0
       0      .1       0  102.79      .1       0     106    .045       0
     124      .1       0
Bank Sta=106,124
XS Rating Curve= 0 ,0
Exp/Cntr(USF)=0,0
Exp/Cntr=0.3,0.1

Type RM Length L Ch R = 1 ,3260    ,202,204,203
XS GIS Cut Line= 2
2175826.35269745330086.9540033452175993.35464203330243.210013242
#Sta/Elev= 30
       0 2016.94      19 2013.41      44  2004.3      63 2001.61      66 1999.92
      69 1997.59      70 1996.27      77 1991.64      88 1977.38      88 1977.12
      88 1976.99      93 1976.38      981977.317     107 1977.28  120.341979.754
     130 1981.09     142 1979.21     160 1981.55     170 1987.83     174 1991.57
     176 1994.13     183 2000.39     186 2002.28     190 2005.84     194 2008.35
     198 2012.04     207 2018.19     214 2024.13     218 2026.77     229 2032.59
#Mann= 4 ,-1 , 0
       0      .1       0      88    .045       0      98      .1       0
  120.34      .1       0
Bank Sta=88,98
XS Rating Curve= 0 ,0
Exp/Cntr(USF)=0,0
Exp/Cntr=0.3,0.1

Type RM Length L Ch R = 1 ,3056    ,127,130,133
XS GIS Cut Line= 2
2175706.77860209330228.1950521992175880.78347413330391.003378024
#Sta/Elev= 30
       0 1998.57      16 1996.32      33 1991.72      41 1990.87      64 1990.69
      71 1989.26     112 1974.59  127.481974.651     140  1973.1     151  1970.1
     155 1968.86     160 1968.54     165 1969.49     167 1971.95     171 1983.05
     174 1989.97     176  1993.8     177 1997.09     180 2002.83     184 2007.88
     191 2015.95     203    2026     212 2035.37     213 2035.77     217 2040.94
     221 2044.77     231 2052.09     235 2055.79     237 2056.79     238 2058.26
#Mann= 4 ,-1 , 0
       0      .1       0  127.48      .1       0     151    .045       0
     165      .1       0
Bank Sta=151,165
XS Rating Curve= 0 ,0
Exp/Cntr(USF)=0,0
Exp/Cntr=0.3,0.1

Type RM Length L Ch R = 1 ,2926    ,173,169,161
XS GIS Cut Line= 2
2175663.32939171330267.2297241292175735.61302734330472.033358391
#Sta/Elev= 30
       0 1994.27      12 1992.72      19  1990.3      23 1986.96      26 1985.09
      30  1981.5      40 1974.79      46  1972.3      66 1971.84      82 1969.55
      95 1966.46     102  1965.6     110 1966.28     120  1967.2     127 1967.08
     133 1969.22     136 1970.76     140 1974.69     141  1974.9     146 1978.63
     151 1983.03     165 1991.56     166 1992.63     167 1992.75     168 1993.76
     182 2001.85     190 2004.45     202 2012.38     207 2014.51     217 2020.93
#Mann= 3 ,-1 , 0
       0      .1       0      95    .045       0     110      .1       0
Bank Sta=95,110
XS Rating Curve= 0 ,0
Exp/Cntr(USF)=0,0
Exp/Cntr=0.3,0.1

Type RM Length L Ch R = 1 ,2758    ,217,217,212
XS GIS Cut Line= 2
2175480.67767401330389.0221263322175656.71746218330541.748701862
#Sta/Elev= 30
       0  2006.5    4.092006.005       9 2004.95      15 2002.33      22 1997.57
      29 1991.26      41 1978.05      43 1976.85      49 1969.69      52 1967.62
      61  1964.7      83 1964.67      96 1960.92      96 1960.87      96 1960.78
     101 1959.83     124  1960.9     133 1963.83     152 1965.06     156 1967.29
     161 1971.84     165 1973.68     187 1974.74     196 1976.97     200 1978.19
  215.471987.865     222 1989.93     229 1994.41     231 1996.76     233 1997.95
#Mann= 5 ,-1 , 0
       0      .1       0    4.09      .1       0      96    .045       0
     124      .1       0  215.47      .1       0
Bank Sta=96,124
XS Rating Curve= 0 ,0
Exp/Cntr(USF)=0,0
Exp/Cntr=0.3,0.1

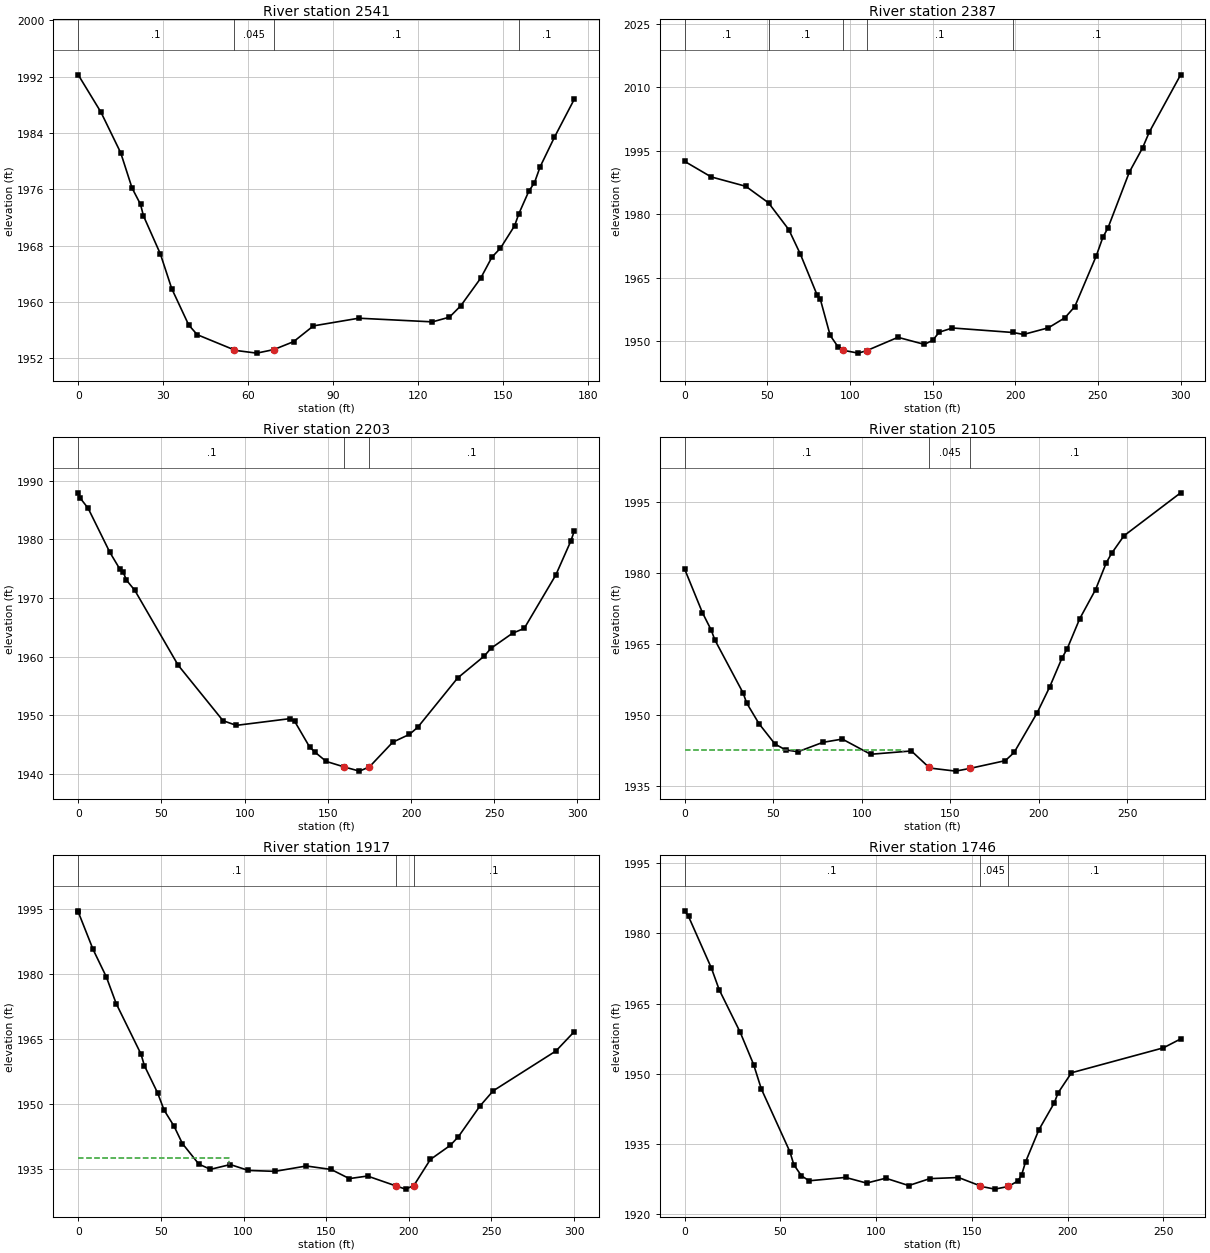
Type RM Length L Ch R = 1 ,2541    ,155,154,155
XS GIS Cut Line= 2
2175422.48968728330618.1734451962175566.33338852330718.681922098
#Sta/Elev= 30
       0 1992.27       8 1986.98      15 1981.19      19 1976.19      22 1973.86
      23 1972.26      29 1966.82      33  1961.9      39 1956.73      42 1955.36
      55 1953.21      55 1953.15      63 1952.74      69 1953.24      76 1954.37
      83 1956.61      99  1957.7     125 1957.18     131 1957.85     135 1959.47
     142 1963.37     146 1966.38     149 1967.65     154 1970.84  155.471972.531
     159 1975.74     161 1976.95     163 1979.21     168 1983.37     175 1988.77
#Mann= 4 ,-1 , 0
       0      .1       0      55    .045       0      69      .1       0
  155.47      .1       0
Bank Sta=55,69
XS Rating Curve= 0 ,0
Exp/Cntr(USF)=0,0
Exp/Cntr=0.3,0.1

Type RM Length L Ch R = 1 ,2387    ,186,184,183
XS GIS Cut Line= 2
 2175271.0172845330689.2843906472175515.19638397330863.573137791
#Sta/Elev= 30
       0 1992.51      16 1988.84      37 1986.61   50.721982.699      63 1976.35
      70 1970.55      80    1961      82 1959.97      88 1951.34      93  1948.5
      961947.807     105 1947.14     110 1947.71     129 1950.88     145 1949.21
     150 1950.17     154  1952.1     162 1953.09  198.621952.022     205 1951.56
     220 1953.13     230  1955.5     236 1958.16     249 1970.17     253 1974.59
     256 1976.71     269 1989.99     277 1995.71     281 1999.41     300 2012.99
#Mann= 5 ,-1 , 0
       0      .1       0   50.72      .1       0      96    .045       0
     110      .1       0  198.62      .1       0
Bank Sta=96,110
XS Rating Curve= 0 ,0
Exp/Cntr(USF)=0,0
Exp/Cntr=0.3,0.1

Type RM Length L Ch R = 1 ,2203    ,101,98,98
XS GIS Cut Line= 2
2175141.68248797330852.7271726662175413.14373927330975.916602444
#Sta/Elev= 30
       0 1987.96       1 1987.14       6  1985.3      19 1977.81      25 1974.95
      27 1974.44      29 1973.05      34 1971.32      60 1958.56      87 1949.07
      95 1948.27     127 1949.41     130 1948.99     139  1944.6     142 1943.76
     149 1942.12     160 1941.16     169 1940.46     175 1941.19     189  1945.4
     199 1946.73     204 1947.94     228 1956.36     244  1960.1     248 1961.42
     261    1964     268 1964.82     287 1973.95     296 1979.73     298 1981.38
#Mann= 3 ,-1 , 0
       0      .1       0     160    .045       0     175      .1       0
Bank Sta=160,175
XS Rating Curve= 0 ,0
Exp/Cntr(USF)=0,0
Exp/Cntr=0.3,0.1

Type RM Length L Ch R = 1 ,2105    ,188,187,188
XS GIS Cut Line= 2
2175097.10757934330944.2864444542175356.12394032331051.507170626
#Sta/Elev= 30
       0 1980.77      10  1971.6      15 1967.88      17 1965.85      33  1954.6
      35 1952.49      42  1948.1      51 1943.82      57 1942.58      64  1942.2
      78 1944.18      89 1944.87     105 1941.66     128 1942.36     138 1938.87
     138 1938.77     153  1938.1     161 1938.67     181 1940.31     186 1942.04
     199 1950.42     206 1955.82     213 1961.97     216 1963.99     223 1970.27
     232 1976.47     238  1982.1     241 1984.09     248 1987.82     280  1996.9
#Mann= 3 ,-1 , 0
       0      .1       0     138    .045       0     161      .1       0
#XS Ineff= 2 , 0
          123.25 1942.58
Permanent Ineff=
       F       F
Bank Sta=138,161
XS Rating Curve= 0 ,0
Exp/Cntr(USF)=0,0
Exp/Cntr=0.3,0.1

Type RM Length L Ch R = 1 ,1917    ,172,172,171
XS GIS Cut Line= 2
2175021.23585269331076.0606851442175279.33619785331228.979656601
#Sta/Elev= 30
       0 1994.53       0 1994.29       9 1985.61      17 1979.29      23  1973.1
      38 1961.45      40 1958.82      48 1952.53      52  1948.5      58 1944.81
      63 1940.83      73 1936.06      80 1934.87      92 1935.97     103 1934.61
     119  1934.4     138 1935.64     153 1934.84     164 1932.73     175 1933.32
     192 1931.07     198  1930.3     203 1931.11     213 1937.14     225 1940.38
     230 1942.41     243 1949.47     251 1952.98     289 1962.19     300 1966.62
#Mann= 3 ,-1 , 0
       0      .1       0     192    .045       0     203      .1       0
#XS Ineff= 2 , 0
           91.23 1937.45
Permanent Ineff=
       F       F
Bank Sta=192,203
XS Rating Curve= 0 ,0
Exp/Cntr(USF)=0,0
Exp/Cntr=0.3,0.1

Type RM Length L Ch R = 1 ,1746    ,225,228,227
XS GIS Cut Line= 2
2174964.36285328331248.8321959692175192.28103291331371.964621883
#Sta/Elev= 30
       0 1984.81       2 1983.62      14 1972.54      18 1967.99      29 1958.88
      36    1952      40 1946.82      55 1933.33      57 1930.61      61 1928.24
      65 1927.18      84  1927.9      95 1926.69     105 1927.73     117 1926.16
     128 1927.64     143 1927.88     154 1926.15     154 1926.04     162  1925.4
     169 1925.97     174 1927.13     176 1928.48     178 1931.19     185 1938.08
     193  1943.8     195 1945.94     202 1950.24     250 1955.56     259 1957.46
#Mann= 3 ,-1 , 0
       0      .1       0     154    .045       0     169      .1       0
Bank Sta=154,169
XS Rating Curve= 0 ,0
Exp/Cntr(USF)=0,0
Exp/Cntr=0.3,0.1

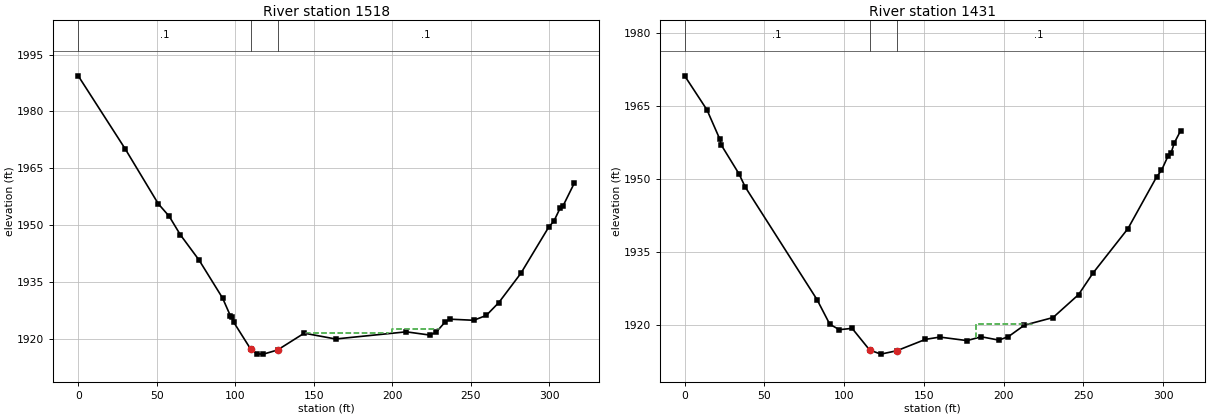
Type RM Length L Ch R = 1 ,1518    ,87,87,86
XS GIS Cut Line= 2
2174823.63449124331346.6653494162175071.80830687331543.035892855
#Sta/Elev= 30
       0 1989.41      30 1970.07      51 1955.62      58 1952.29      65 1947.47
      77 1940.74      92  1930.7      97 1925.98      98  1925.8      99 1924.38
     110 1917.15     114 1915.97     118  1915.9     127 1916.99     144 1921.43
     164  1919.9     209 1921.79     224 1920.94     228 1921.65     234 1924.49
     237 1925.13     252 1924.84     260 1926.12     268 1929.52     282 1937.22
     300 1949.59     303 1950.95     307 1954.41     309 1955.12     316 1960.99
#Mann= 3 ,-1 , 0
       0      .1       0     110    .045       0     127      .1       0
#XS Ineff= 2 ,-1
  144.31   197.1 1921.45  200.22  230.59  1922.6
Permanent Ineff=
       F       F
Bank Sta=110,127
XS Rating Curve= 0 ,0
Exp/Cntr(USF)=0,0
Exp/Cntr=0.3,0.1

Type RM Length L Ch R = 1 ,1431    ,149,151,154
XS GIS Cut Line= 2
2174759.78394644331411.720621475 2175010.3672166331596.043892311
#Sta/Elev= 30
       0 1971.21      14 1964.21      22 1958.23      23 1956.98      34 1951.12
      38 1948.37      83 1925.27      91 1920.21      97  1919.1     105 1919.37
     116 1914.92     123 1914.08     1331914.775     151 1917.11     160 1917.58
     177 1916.86     186 1917.64     197 1916.96     203 1917.67     213 1920.02
     231 1921.59     247  1926.3     256  1930.7     278 1939.86     296 1950.49
     299  1951.8     303 1954.67     305 1955.35     307 1957.42     311 1959.94
#Mann= 3 ,-1 , 0
       0      .1       0     116    .045       0     133      .1       0
#XS Ineff= 1 ,-1
  182.57  219.04 1920.18
Permanent Ineff=
       F
Bank Sta=116,133
XS Rating Curve= 0 ,0
Exp/Cntr(USF)=0,0
Exp/Cntr=0.3,0.1