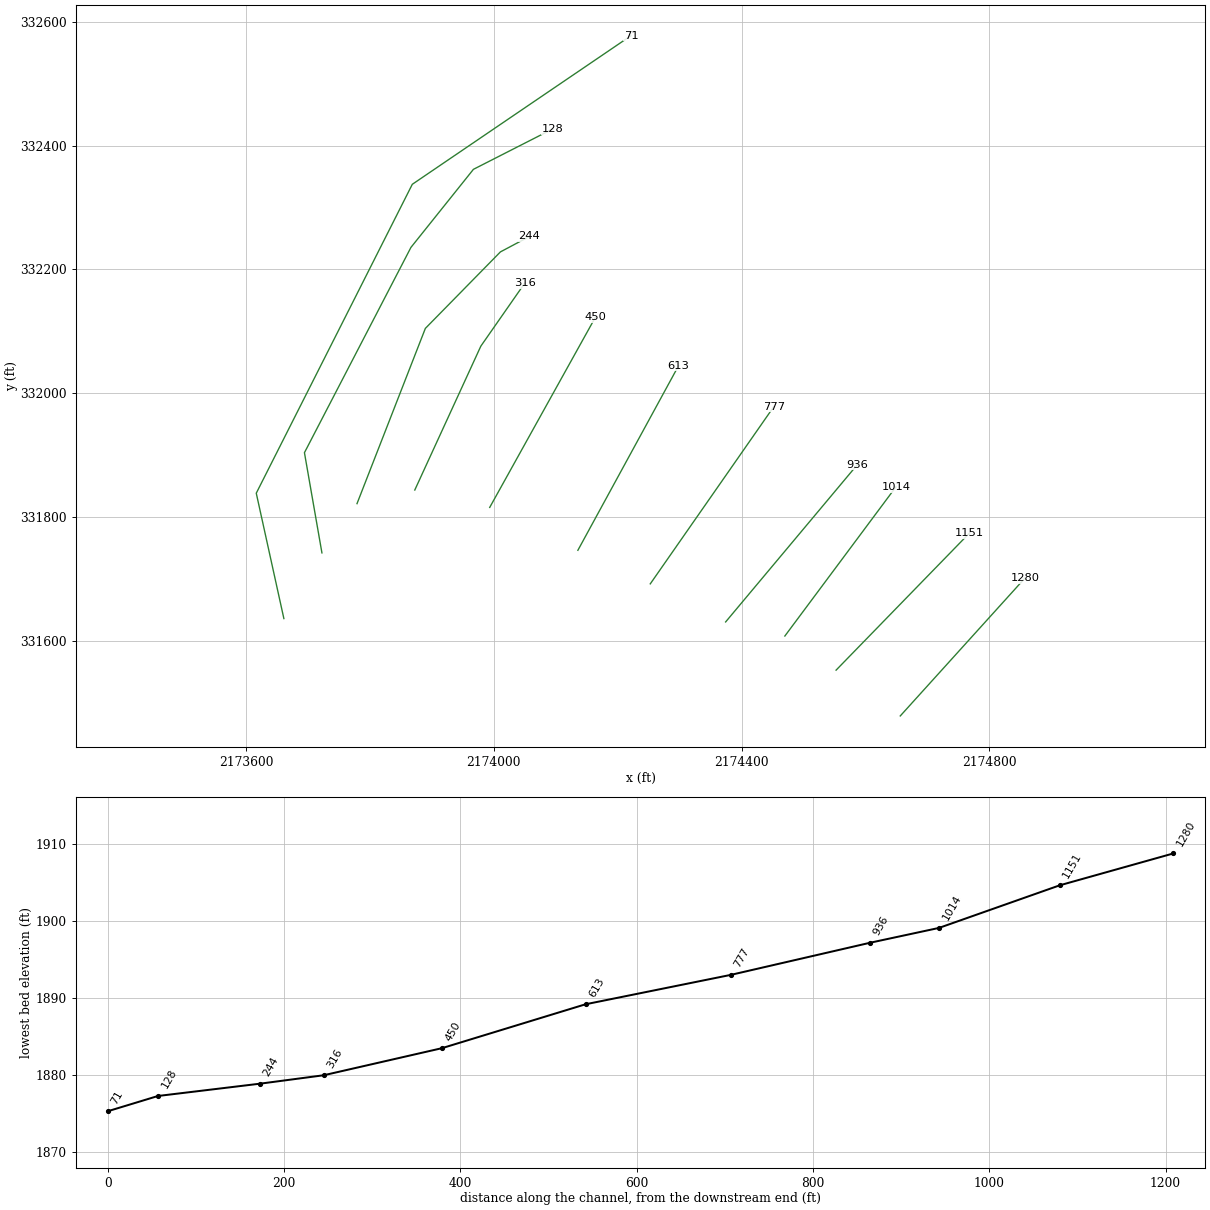
HEC-RAS study ANTNYCKT1.prj: ANTNYCKT1

--- ANTNYCKT1.g02 (geometry) --- (continued)

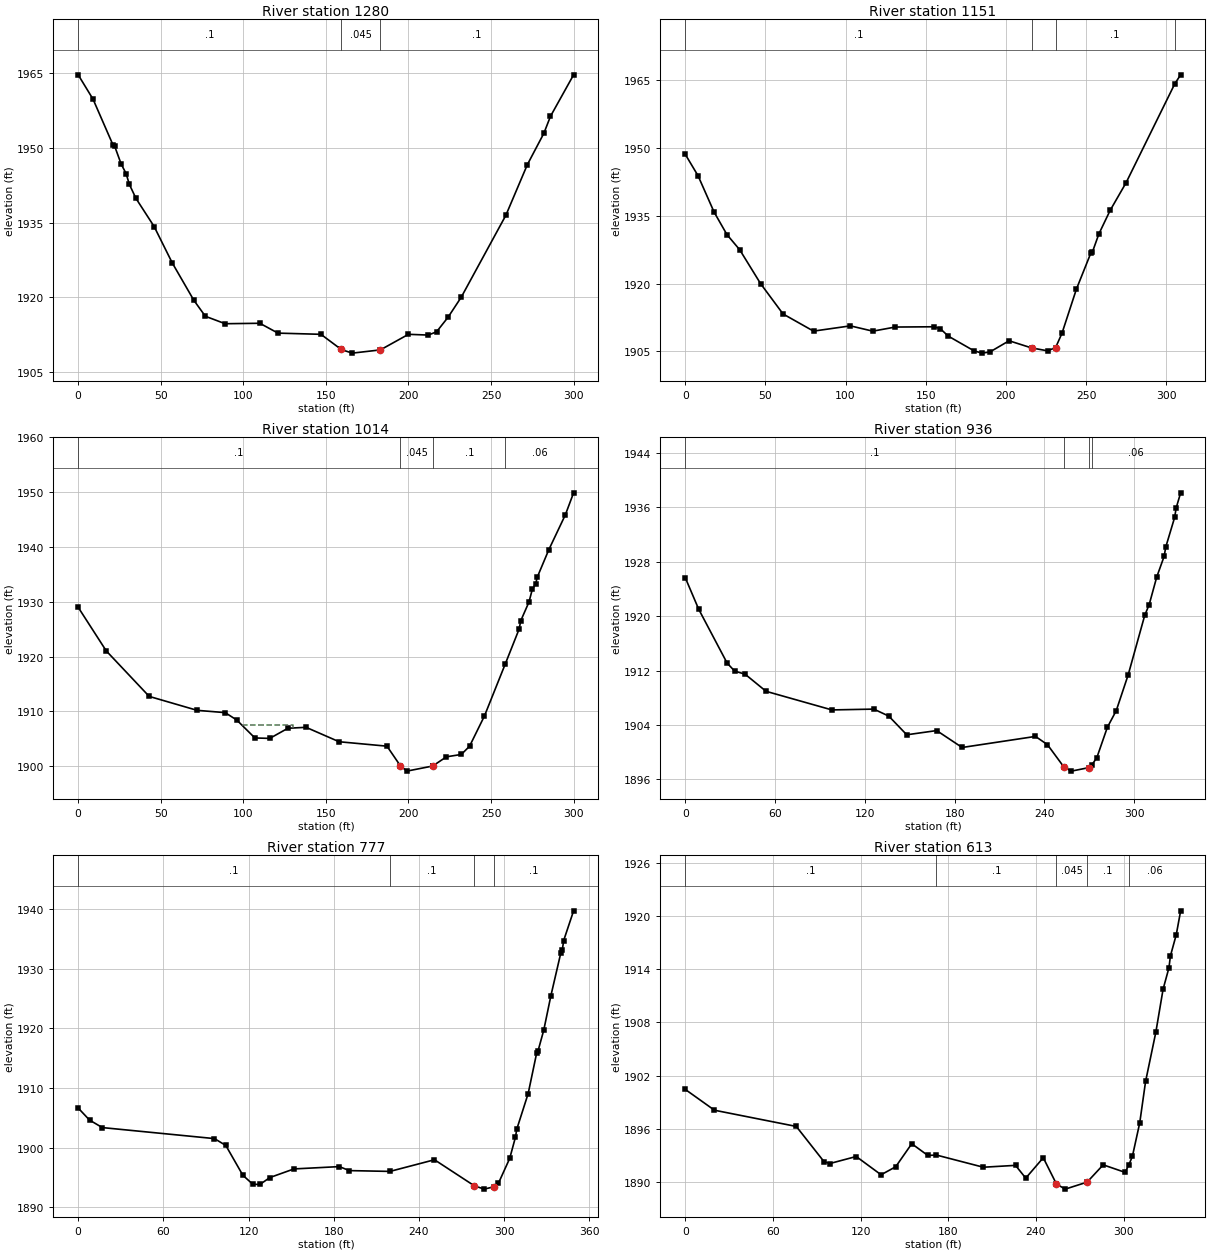
Type RM Length L Ch R = 1 ,1280    ,129,129,125
XS GIS Cut Line= 2
2174656.17740205331479.185348056 2174857.4737252  331701.7127559
#Sta/Elev= 30
       0 1964.71       9 1959.81      21 1950.68      22 1950.45      26  1946.8
      29 1944.87      31 1942.68      35 1939.87      46 1934.22      57 1926.89
      70 1919.42      77 1916.19      89 1914.69     110 1914.78     121  1912.8
     147 1912.56     159 1909.59     159 1909.53     166 1908.78     183 1909.43
     200 1912.56     212 1912.41     217 1913.06     224    1916     232 1920.04
     259 1936.49     272 1946.66     282 1952.96     286 1956.37     300 1964.71
#Mann= 3 ,-1 , 0
       0      .1       0     159    .045       0     183      .1       0
Bank Sta=159,183
XS Rating Curve= 0 ,0
Exp/Cntr(USF)=0,0
Exp/Cntr=0.3,0.1

Type RM Length L Ch R = 1 ,1151    ,135,137,136
XS GIS Cut Line= 2
2174552.58007362331553.1400455662174767.88708006331774.402352185
#Sta/Elev= 30
       0 1948.55       8  1943.8      18 1935.78      26 1930.82      34 1927.45
      47 1919.98      61 1913.29      80  1909.5     103 1910.66     117 1909.49
     131  1910.4     155 1910.46     159 1910.07     164 1908.41     180 1905.17
     185 1904.64     190 1904.89     202 1907.37     216 1905.79     226 1905.15
     231 1905.86     235 1909.04     244 1918.79     253 1926.75     254    1927
     258 1930.96     265 1936.14     275 1942.29  305.411964.157     309 1966.09
#Mann= 4 ,-1 , 0
       0      .1       0     216    .045       0     231      .1       0
  305.41     .06       0
Bank Sta=216,231
XS Rating Curve= 0 ,0
Exp/Cntr(USF)=0,0
Exp/Cntr=0.3,0.1

Type RM Length L Ch R = 1 ,1014    ,79,78,77
XS GIS Cut Line= 2
2174469.88497811331608.2441498622174649.08219346331848.844145723
#Sta/Elev= 30
       0 1928.99      17 1921.04      43 1912.74      72  1910.2      89 1909.78
      96 1908.44     107 1905.16     116 1905.08     127 1906.93     138  1907.1
     158 1904.47     187 1903.66     195 1900.13     199 1899.11     215 1900.06
     215 1900.11     223 1901.72     232 1902.15     237 1903.65     246 1909.16
  258.671918.689     267 1925.01     268 1926.53     273 1929.97     275 1932.27
     277 1933.24     278 1934.48     285  1939.5     295 1945.85     300 1949.87
#Mann= 4 ,-1 , 0
       0      .1       0     195    .045       0     215      .1       0
  258.67     .06       0
#XS Ineff= 1 ,-1
   99.82   130.31907.556
Permanent Ineff=
       F
Bank Sta=195,215
XS Rating Curve= 0 ,0
Exp/Cntr(USF)=0,0
Exp/Cntr=0.3,0.1

Type RM Length L Ch R = 1 ,936     ,158,158,159
XS GIS Cut Line= 2
2174374.27122312331630.9809828622174586.89270122331884.884054277
#Sta/Elev= 30
       0 1925.68       9 1921.02      28 1913.09      33 1911.92      40 1911.46
      54 1908.94      98  1906.2     126 1906.32     136 1905.29     148 1902.54
     168 1903.16     185 1900.67     234  1902.3     242 1901.09     2531897.795
     258 1897.19     270 1897.72  271.511898.052     275 1899.17     282 1903.62
     288 1906.11     296  1911.4     307 1920.12     310 1921.72     315 1925.75
     320 1928.83     321 1930.14     327 1934.55     328 1935.93     331 1938.16
#Mann= 4 ,-1 , 0
       0      .1       0     253    .045       0     270      .1       0
  271.51     .06       0
Bank Sta=253,270
XS Rating Curve= 0 ,0
Exp/Cntr(USF)=0,0
Exp/Cntr=0.3,0.1

Type RM Length L Ch R = 1 ,777     ,163,165,163
XS GIS Cut Line= 2
2174252.59376983 331692.422073142174452.07713711331978.617486711
#Sta/Elev= 30
       0 1906.63       8 1904.61      17 1903.35      96  1901.5     104 1900.35
     116 1895.35     123 1893.84     128  1893.8     135 1894.96     152 1896.41
     184  1896.8     191 1896.13  219.631895.994     251 1897.95     279 1893.59
     286 1893.02     293 1893.42     296 1893.98     304 1898.18     308  1901.7
     309  1903.1     317 1909.06     323 1915.88     324 1916.26     328 1919.72
     333 1925.48     340 1932.67     341 1933.09     342 1934.74     349 1939.73
#Mann= 4 ,-1 , 0
       0      .1       0  219.63      .1       0     279    .045       0
     293      .1       0
Bank Sta=279,293
XS Rating Curve= 0 ,0
Exp/Cntr(USF)=0,0
Exp/Cntr=0.3,0.1

Type RM Length L Ch R = 1 ,613     ,162,163,161
XS GIS Cut Line= 2
2174135.73522557331746.6347998572174298.23482311332044.535115049
#Sta/Elev= 30
       0 1900.45      20  1898.1      76 1896.27      95 1892.29      99 1892.09
     117 1892.88     134 1890.82     144 1891.72     155 1894.32     166    1893
   171.91893.043     204 1891.67     226 1891.88     233 1890.44     245 1892.74
     254 1889.78     260  1889.2     275 1889.99     286 1891.94     301 1891.09
  303.621891.959     306 1892.91     311 1896.67     315 1901.34     322 1906.88
     327 1911.76     331 1914.17     332  1915.5     336  1917.9     339 1920.59
#Mann= 5 ,-1 , 0
       0      .1       0   171.9      .1       0     254    .045       0
     275      .1       0  303.62     .06       0
Bank Sta=254,275
XS Rating Curve= 0 ,0
Exp/Cntr(USF)=0,0
Exp/Cntr=0.3,0.1

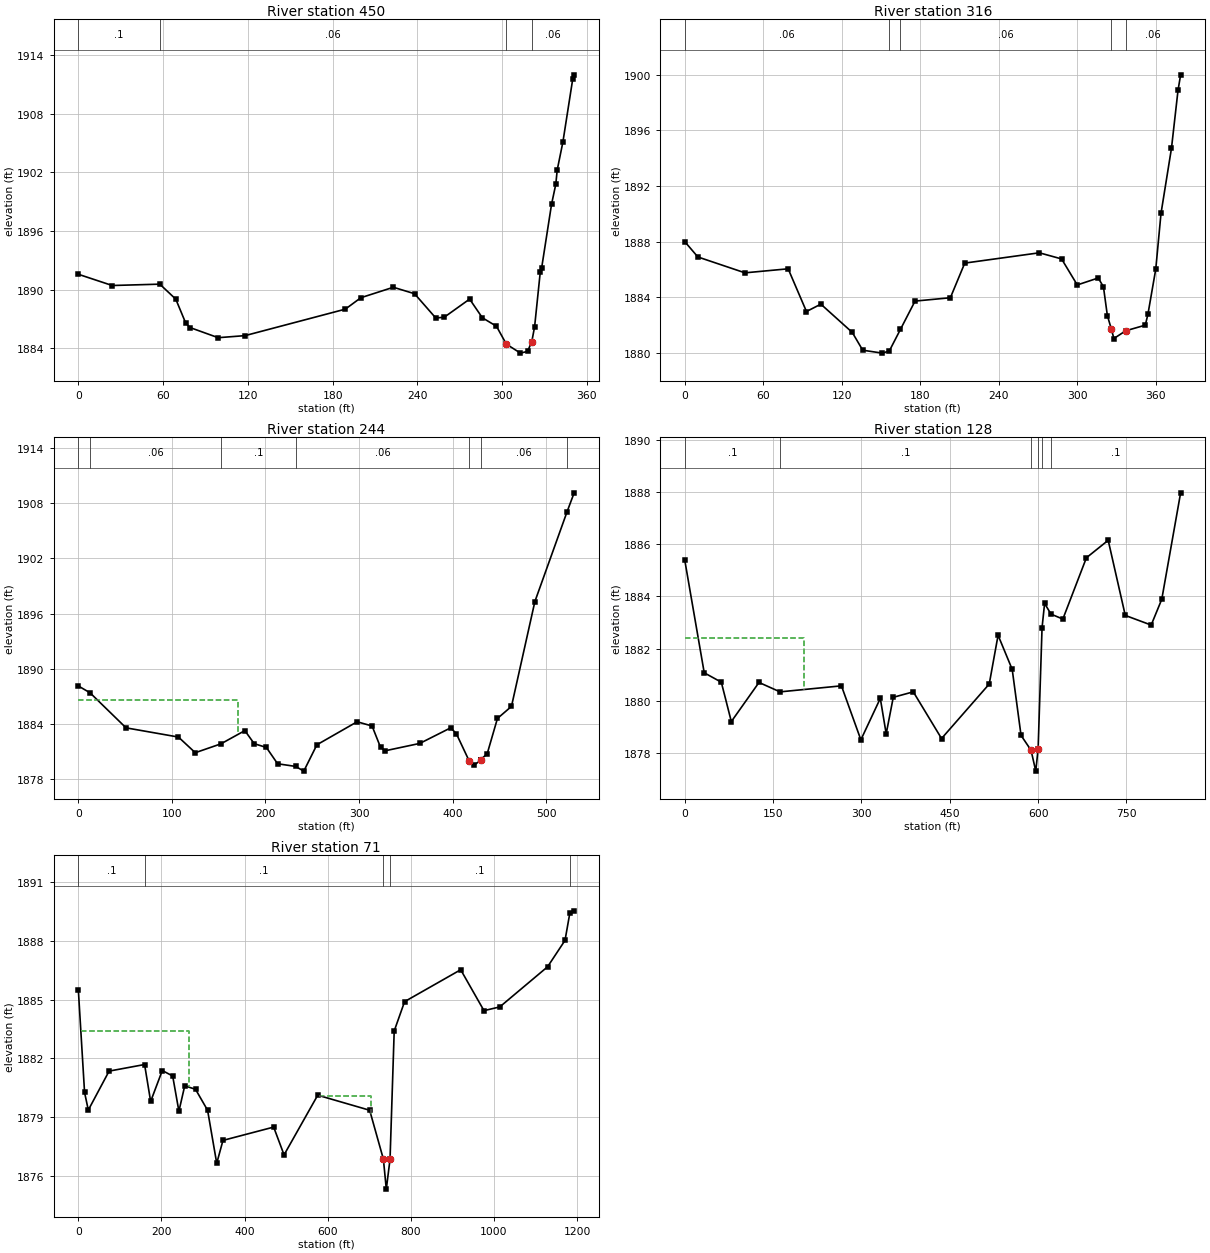
Type RM Length L Ch R = 1 ,450     ,133,134,133
XS GIS Cut Line= 2
2173993.39565362331815.8588466912174163.81515814332122.502883594
#Sta/Elev= 30
       0 1891.57      24 1890.42   57.681890.558      69 1889.02      76 1886.58
      79 1886.12      99 1885.08     118 1885.29     189    1888     200 1889.17
     223 1890.24     238 1889.58     253  1887.1     259 1887.17     277 1889.03
     286 1887.12     296 1886.25     303 1884.42     313  1883.5     318 1883.68
     321 1884.67     323  1886.2     327 1891.79     328 1892.23     335 1898.74
     338 1900.78     339 1902.24     343 1905.08     350 1911.56     351 1911.98
#Mann= 4 ,-1 , 0
       0      .1       0   57.68     .06       0     303    .045       0
     321     .06       0
Bank Sta=303,321
XS Rating Curve= 0 ,0
Exp/Cntr(USF)=0,0
Exp/Cntr=0.3,0.1

Type RM Length L Ch R = 1 ,316     ,73,72,71
XS GIS Cut Line= 3
2173872.42270146331843.9085643592173979.03883144 332076.17721826
2174049.79432976332177.692415033
#Sta/Elev= 30
       0    1888      10  1886.9      46 1885.76      79 1886.05      93 1882.98
     104 1883.51     128 1881.48     136  1880.2     151 1879.99  156.341880.147
  164.831881.696     176 1883.73     203 1883.97     214 1886.46     271  1887.2
     288 1886.76     300 1884.89     316 1885.39     320 1884.76     323 1882.69
     326 1881.73     328 1881.04     3371881.595     352    1882     354 1882.78
     360 1886.03     364 1890.03     372 1894.71     377 1898.87     379 1899.99
#Mann= 5 ,-1 , 0
       0     .06       0  156.34      .1       0  164.83     .06       0
     326    .045       0     337     .06       0
Bank Sta=326,337
XS Rating Curve= 0 ,0
Exp/Cntr(USF)=0,0
Exp/Cntr=0.3,0.1

Type RM Length L Ch R = 1 ,244     ,114,116,116
XS GIS Cut Line= 4
 2173779.1359565 331821.930253632173889.48046418332104.835895782
2174010.62708731332228.3246431822174057.42795365 332253.22261284
#Sta/Elev= 30
       0 1888.15   12.511887.405      51  1883.6     107  1882.6     125  1880.9
  152.431881.863     178  1883.3     188 1881.88     201 1881.47     213  1879.7
  232.261879.411     241  1878.9     255 1881.76     298 1884.26     314  1883.8
     323 1881.49     328 1881.11     365 1881.91     398  1883.6     404 1882.98
     418 1879.96     423 1879.54     430 1880.08     430 1880.16     437 1880.77
     448 1884.62     463 1885.93     488 1897.31   522.51907.088     530 1909.12
#Mann= 7 ,-1 , 0
       0      .1       0   12.51     .06       0  152.43      .1       0
  232.26     .06       0     418    .045       0     430     .06       0
   522.5      .1       0
#XS Ineff= 2 , 0
          170.76 1886.67
Permanent Ineff=
       F       F
Bank Sta=418,430
XS Rating Curve= 0 ,0
Exp/Cntr(USF)=0,0
Exp/Cntr=0.3,0.1

Type RM Length L Ch R = 1 ,128     ,56,57,59
XS GIS Cut Line= 5
2173722.51377527331742.4182544462173694.28444399331904.223664369
2173866.19528869332235.5911119782173967.07340912332361.648066273
2174094.77449872332426.703338333
#Sta/Elev= 30
       0 1885.38      33 1881.07      62 1880.71      79  1879.2     126  1880.7
   161.71880.339     266 1880.57     299  1878.5     332 1880.09     342 1878.73
     354 1880.13     388 1880.34     436 1878.55     517 1880.64     532 1882.51
     556  1881.2     571 1878.67     588  1878.1     596  1877.3     600 1878.15
  606.691882.801     611 1883.73  621.811883.321     642 1883.13     682 1885.48
     719 1886.15     748 1883.27     792  1882.9     810 1883.89     842 1887.97
#Mann= 6 ,-1 , 0
       0      .1       0   161.7      .1       0     588    .045       0
     600      .1       0  606.69     .06       0  621.81      .1       0
#XS Ineff= 2 , 0
          202.18 1882.41
Permanent Ineff=
       F       F
Bank Sta=588,600
XS Rating Curve= 0 ,0
Exp/Cntr(USF)=0,0
Exp/Cntr=0.3,0.1

Type RM Length L Ch R = 1 ,71      ,71,71,71
XS GIS Cut Line= 5
2173661.07268499331636.4022555332173616.49777635331838.796435275
 2173767.5145318332137.6502260862173868.41038586332337.490606637
2174221.27086106332577.294245878
#Sta/Elev= 30
       0 1885.51      15 1880.26      24 1879.36      74 1881.35  159.421881.687
     174  1879.8     202 1881.38     227  1881.1     242  1879.3     256  1880.6
     282 1880.42     311 1879.35     333 1876.64     348 1877.81     470 1878.49
     495 1877.07     576 1880.12     701 1879.35     734 1876.85     741 1875.32
     750 1876.85     760  1883.4     785  1884.9     920 1886.53     976 1884.44
    1014 1884.63    1129 1886.68    1171 1888.03 1182.661889.433    1193 1889.54
#Mann= 5 ,-1 , 0
       0      .1       0  159.42      .1       0     734    .045       0
     750      .1       0 1182.66     .06       0
#XS Ineff= 2 ,-1
    5.41  266.67 1883.39  580.18   704.5 1880.09
Permanent Ineff=
       F       F
Bank Sta=734,750
XS Rating Curve= 0 ,0
Exp/Cntr(USF)=0,0
Exp/Cntr=0.3,0.1
LCMann Table=0

Chan Stop Cuts=-1
Use User Specified Reach Order=0
Composite Channel Slope=5